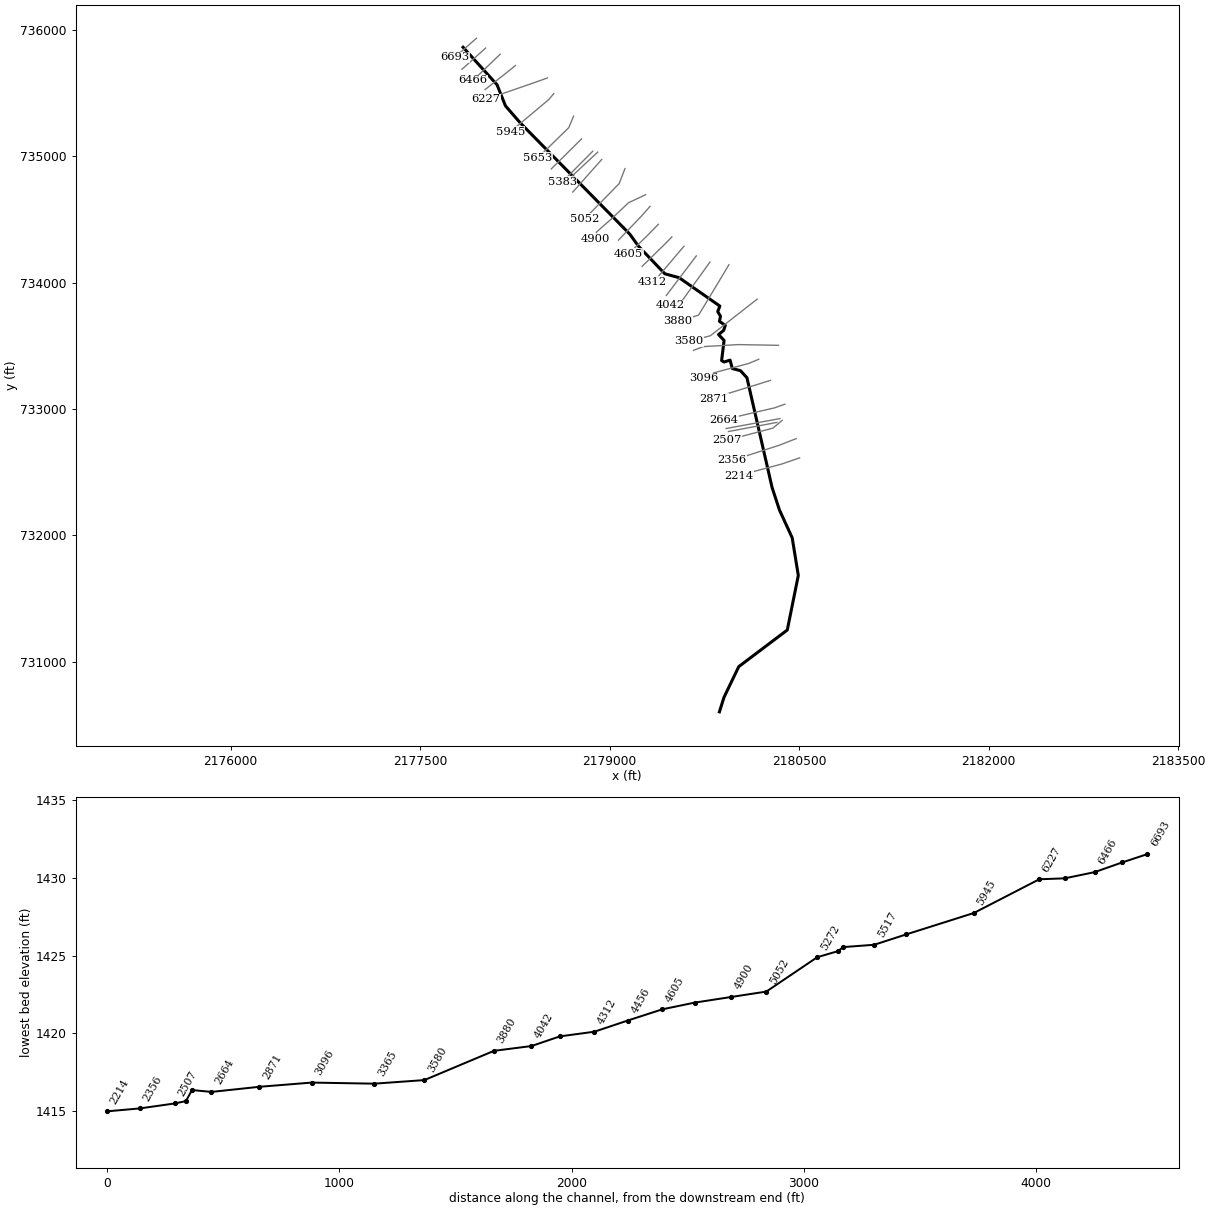
--- MUDLK.prj (project) ---

Proj Title=MUDLK
Current Plan=p01
Default Exp/Contr=0,0
English Units
Geom File=g01
Flow File=f01
Plan File=p01
BEGIN DESCRIPTION:
---------- MODELED AS PART OF WVEMD CTP PROGRAM, 2023----------
Stream Name: Mud Lick
Flood Zone:  AFH
Upshur County, WV
HEC-RAS Version: RAS 6.3
Vertical Datum: NAVD88
Projection: NAD 1983 StatePlane West Virginia S FIPS 4702 (US Feet)
Terrain: 1-meter LIDAR (FEMA Region III 3DEP collected 2016-2018)
Land Use: 2019 NLCD
Hydrologic Method:
Gage-Weighted WV 2010 RRE
Additional Model Notes:
None
END DESCRIPTION:
DSS Export Rating Curves= 0
DSS Export Rating Curve Sorted= 0
DSS Export Volume Flow Curves= 0
DXF OffsetX= 0
DXF OffsetY= 0
DXF ScaleX= 0
DXF ScaleY= 0

--- MUDLK.p01 (plan) ---

Plan Title=Floodplain
Program Version=6.30
Short Identifier=Floodplain
Geom File=g01
Flow File=f01
Subcritical Flow
K Sum by GR= 0
Std Step Tol= 0.01
Critical Tol= 0.01
Num of Std Step Trials= 20
Max Error Tol= 0.3
Flow Tol Ratio= 0.001
Split Flow NTrial= 30
Split Flow Tol= 0.02
Split Flow Ratio= 0.02
Log Output Level= 0
Friction Slope Method= 1
Unsteady Friction Slope Method= 2
Unsteady Bridges Friction Slope Method= 1
Parabolic Critical Depth
Global Vel Dist= 0 , 0 , 0
Global Log Level= 0
CheckData=False
Encroach Param=-1 ,0,0, 0
Mapping Interval=1HOUR
Computation Time Step Use Courant=        0
Computation Time Step Use Time Series=    0
Computation Time Step Count To Double=0
Computation Time Step Max Doubling=0
Computation Time Step Max Halving=0
Computation Time Step Residence Courant=0
Run HTab= 0
Run UNet= 0
Run Sediment= 0
Run PostProcess= 0
Run WQNet= 0
Run RASMapper=-1
UNET Theta= 0
UNET Theta Warmup= 0
UNET ZTol= 0
UNET ZSATol= 0
UNET MxIter= 0
UNET Max Iter WO Improvement= 0
UNET MaxInSteps= 0
UNET DtIC= 0
UNET DtMin= 0
UNET MaxCRTS= 0
UNET WFStab= 0
UNET SFStab= 0
UNET WFX= 1
UNET SFX= 1
UNET Gravity=32.17405
UNET 1D Methodology=Finite Difference
UNET DSS MLevel= 1
UNET Pardiso=0
UNET DZMax Abort= 0
UNET Use Existing IB Tables= 0
UNET Froude Reduction=False
UNET Froude Limit= 0
UNET Froude Power= 0
UNET D1 Cores= 0
UNET WindReference=Eulerian
UNET WindDragFormulation=Hsu (1988)
UNET D2 Coriolis=0
UNET D2 Cores= 0
UNET D2 Theta= 1
UNET D2 Theta Warmup= 1
UNET D2 Z Tol= 0.01
UNET D2 Volume Tol= 0.01
UNET D2 Max Iterations= 20
UNET D2 Equation= 0
UNET D2 RampUpFraction=0.1
UNET D2 TimeSlices= 1
UNET D2 Turbulence Formulation=Non-Conservative (original)
UNET D2 Eddy Viscosity=0.3
UNET D2 Transverse Eddy Viscosity=0.1
UNET D2 Smagorinsky Mixing=0
UNET D2 BCVolumeCheck=0
UNET D2 Cores=0
UNET D2 SolverType=PARDISO (Direct)
UNET D2 Minimum Iterations= 3
UNET D2 Maximum Iterations= 30
UNET D2 Restart Number= 10
UNET D2 Relaxation Coeff=1.3
UNET D2 SOR Precondition Iterations= 10
UNET D2 ILUT Maximum Fill= 8
UNET D2 ILUT Tolerance=1E-08
UNET D2 Convergence Tolerance=0.00001
UNET D1D2 MaxIter= 0
UNET D1D2 ZTol=0.01
UNET D1D2 QTol=0.1
UNET D1D2 MinQTol=1
Write IC File= 0
Write IC File at Fixed DateTime=0
Write IC File at Sim End=0
Echo Input=False
Echo Parameters=False
Echo Output=False
Write Detailed= 0
HDF Write Warmup=0
HDF Write Time Slices=0
HDF Flush=0
HDF Compression= 1
HDF Chunk Size= 1
HDF Spatial Parts= 1
HDF Use Max Rows=0
HDF Fixed Rows= 1
Calibration Method= 0
Calibration Iterations= 20
Calibration Max Change=0.05
Calibration Tolerance=0.2
Calibration Maximum=1.5
Calibration Minimum=0.5
Calibration Optimization Method= 1
WQ AD Non Conservative
WQ ULTIMATE=-1
WQ Max Comp Step=1HOUR
WQ Output Interval=15MIN
WQ Output Selected Increments= 0
WQ Output face flow=0
WQ Output face velocity=0
WQ Output face area=0
WQ Output face dispersion=0
WQ Output cell volume=0
WQ Output cell surface area=0
WQ Output cell continuity=0
WQ Output cumulative cell continuity=0
WQ Output face conc=0
WQ Output face dconc_dx=0
WQ Output face courant=0
WQ Output face peclet=0
WQ Output face adv mass=0
WQ Output face disp mass=0
WQ Output cell mass=0
WQ Output cell source sink temp=0
WQ Output nsm pathways=0
WQ Output nsm derived pathways=0
WQ Create Restart=0
WQ Fixed Restart=0
WQ System Summary=0
WQ Write To DSS=0
Sorting and Armoring Iterations= 10
XS Update Threshold= 0.02
Bed Roughness Predictor= 0
Hydraulics Update Threshold= 0.02
Energy Slope Method= 1
Volume Change Method= 1
Sediment Retention Method= 0
Sediment TS Multiplier= 1
Warm Up Method= 0
XS Weighting Method= 0
Number of US Weighted Cross Sections= 1
Number of DS Weighted Cross Sections= 1
Upstream XS Weight=0
Main XS Weight=1
Downstream XS Weight=0
Number of DS XS's Weighted with US Boundary= 1
Upstream Boundary Weight= 1
Weight of XSs Associated with US Boundary= 0
Number of US XS's Weighted with DS Boundary= 1
Downstream Boundary Weight= 0.5
Weight of XSs Associated with DS Boundary= 0.5
Percentile Method= 0
Sediment Output Level= 3
Mass or Volume Output= 0
Output Increment Type= 1
Profile and TS Output Increment= 1
Transport Output Increment 1
XS Output Flag= 0
XS Output Increment= 10
Read HDF5 Sediment Hotstart= 0
Sediment Hotstart Type= 0
Write Gradation File= 0
Read Gradation Hotstart= 0
Write HDF5 File= 1
Write Binary Output= 1
Write DSS Sediment File= 0
DSS Sediment Output Type= 1
SV Curve= 0
Specific Gage Flag= 0
Subcell Erosion Methods= 0
Subcell Deposition Methods= 0
Advection Scheme= 1
Matrix Solver= 0
Implicit Weighting Factor= 1
Maximum Outer Loop Convergence Iterations= 5
Convergence Maximum Absolute= 0.001
Convergence RMSE= 0.0001
Grain Fractions Max Abs Error= 0.001
Max Subgrid Regions= 1
Max Subgrid Length Scale= 3.402823E+38
Initial Layer Thickness= 3.402823E+38
Min Layer Thickness= 3.402823E+38
Max Layer Thickness= 3.402823E+38
Number of Layers= 5

--- MUDLK.f01 (steady flow) ---

Flow Title=Flows
Program Version=6.31
Number of Profiles= 1
Profile Names=01pct
River Rch & RM=MUDLK,Main            ,6693
     366
River Rch & RM=MUDLK,Main            ,3365
     446
River Rch & RM=MUDLK,Main            ,3096
     496
Boundary for River Rch & Prof#=MUDLK,Main            , 1
Up Type= 0
Dn Type= 3
Dn Slope=0.00316
DSS Import GetInterval= 0
DSS Import GetPeak= 0
DSS Import FillOption= 0

--- MUDLK.g01 (geometry) ---

Geom Title=Geometry
Program Version=6.31

River Reach=MUDLK           ,Main
Reach XY= 30
     2177839.205      735861.595     2178108.371      735564.299
     2178174.675      735397.838     2178291.344      735263.598
     2179158.277      734383.644     2179227.043      734288.209
     2179435.999      734069.608     2179549.635      734038.102
     2179871.941      733813.921     2179855.115      733770.109
     2179876.835      733733.623     2179868.851      733692.473
     2179915.209      733661.567     2179901.874      733621.561
     2179861.868      733588.538     2179905.308      733541.636
     2179885.792      733382.185     2179905.308      733371.368
     2179952.811      733386.106     2179970.754      733319.458
     2180035.141      733302.861     2180086.278      733247.001
     2180285.591      732377.493     2180343.368       732201.33
     2180444.555      731980.755     2180492.917      731682.629
      2180405.58      731250.951     2180021.548      730961.411
2179904.25551154730717.6426940622179868.52709666730603.503256352

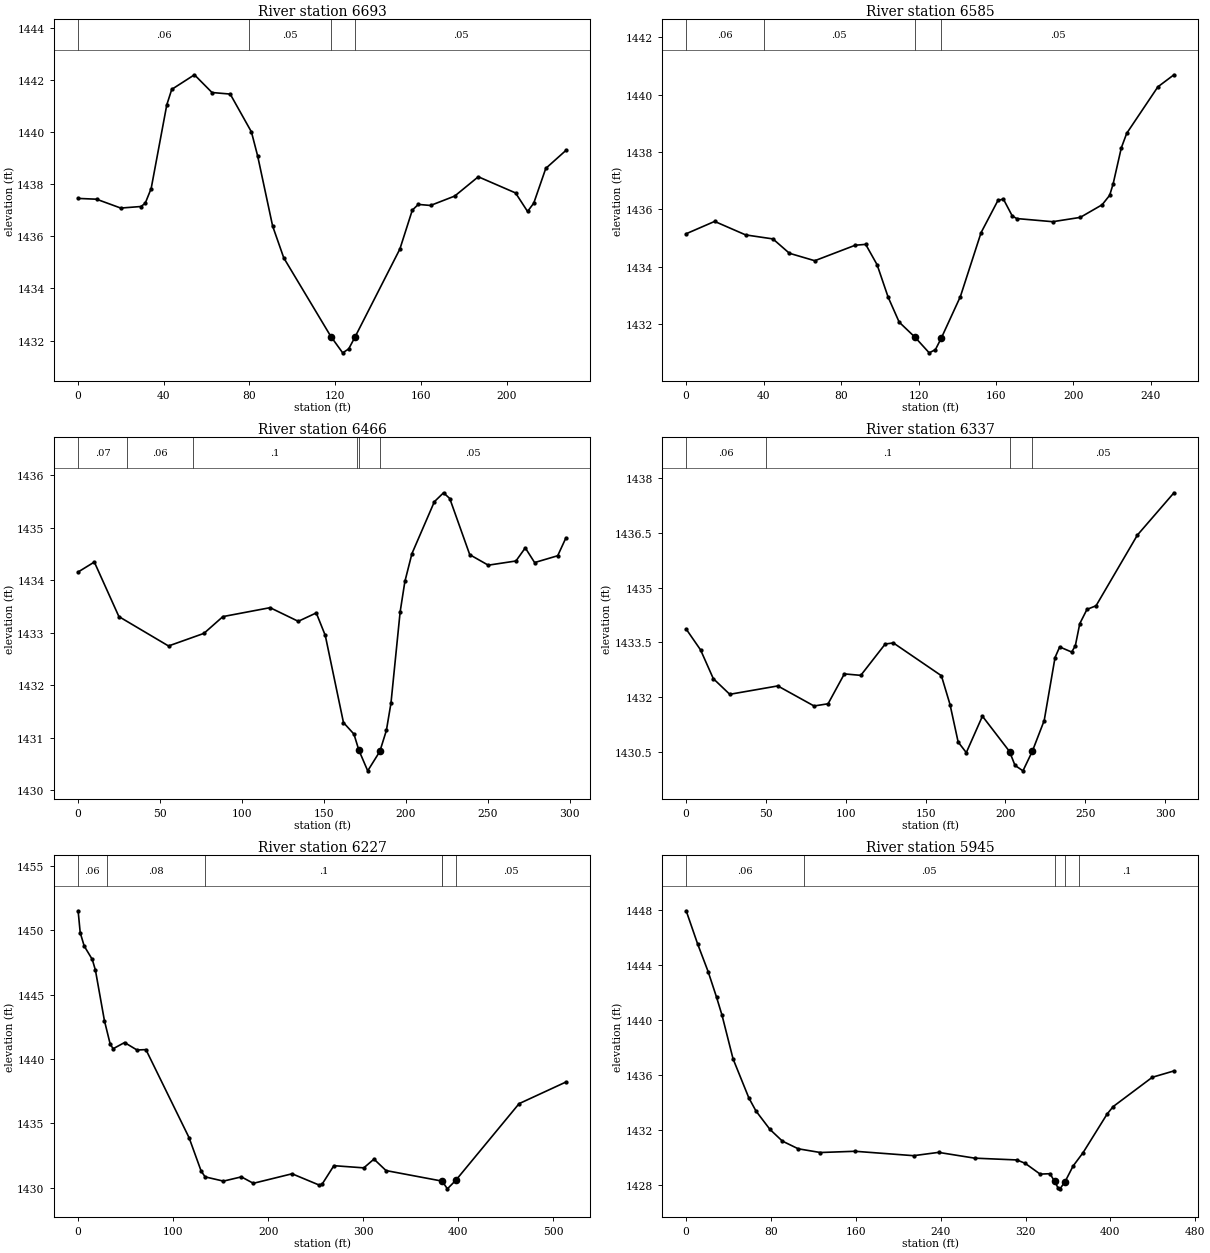
Type RM Length L Ch R = 1 ,6693    ,107.7,107.7,107.7
XS GIS Cut Line= 2
2177944.96013038735932.5383386532177773.94988301735782.202883008
#Sta/Elev= 30
       0 1437.45     8.6 1437.42    19.9 1437.08    29.3 1437.14    31.3 1437.26
    34.1 1437.83    41.4 1441.04    43.7 1441.63    54.3 1442.19    62.5 1441.51
      71 1441.45    80.9    1440    83.8 1439.08    90.8 1436.39      96 1435.17
     1181432.155   123.5 1431.53   126.3 1431.68   129.31432.143   150.2 1435.51
     156    1437   158.8 1437.22   164.5 1437.18   175.8 1437.54   186.8 1438.28
   204.2 1437.66   209.8 1436.95   212.7 1437.27   218.3  1438.6   227.7 1439.29
#Mann= 4 ,-1,0
       0     .06       0      80     .05       0     118    .045       0
   129.3     .05       0
Bank Sta=118,129.3
XS Rating Curve= 0 ,0
Exp/Cntr=0.3,0.1

Type RM Length L Ch R = 1 ,6585    ,119.1,119.6,119.9
XS GIS Cut Line= 2
2178017.68507548735854.9761253382177829.95203685735687.009666623
#Sta/Elev= 30
       0 1435.15    14.7 1435.58    30.7 1435.11    44.8 1434.97    53.3 1434.47
    66.4 1434.21    87.3 1434.75    92.7 1434.78    98.6 1434.07   104.3 1432.94
     110 1432.07   118.21431.542   125.5    1431   128.7 1431.11   131.81431.521
   141.6 1432.96   152.3 1435.19     161 1436.31   163.8 1436.36   168.4 1435.77
   170.7 1435.68   189.3 1435.57   203.5 1435.72   214.8 1436.16   218.7 1436.49
   220.5 1436.89   224.7 1438.14   227.5 1438.65   243.6 1440.27   251.9 1440.69
#Mann= 4 ,-1,0
       0     .06       0      40     .05       0   118.2    .045       0
   131.8     .05       0
Bank Sta=118.2,131.8
XS Rating Curve= 0 ,0
Exp/Cntr=0.3,0.1

Type RM Length L Ch R = 1 ,6466    ,130.1,128.9,127.7
XS GIS Cut Line= 2
2178132.96766819735806.436086303 2177918.2968829735600.033869835
#Sta/Elev= 30
       0 1434.16     9.9 1434.35    24.9 1433.31    55.2 1432.75    76.8 1432.99
    88.4 1433.31   117.2 1433.48   134.4 1433.22   145.4 1433.38   150.9 1432.95
     162 1431.29   168.4 1431.07   171.41430.764   176.8 1430.37   184.2 1430.74
   188.2 1431.14     191 1431.66   196.6  1433.4   199.5 1433.98   203.8 1434.51
   217.5  1435.5   223.1 1435.67   226.9 1435.56   239.1 1434.49   250.4 1434.29
   267.3 1434.37     273 1434.62   278.7 1434.34   292.8 1434.47   297.8 1434.81
#Mann= 6 ,-1,0
       0     .07       0      30     .06       0      70      .1       0
     170     .05       0   171.4    .045       0   184.2     .05       0
Bank Sta=171.4,184.2
XS Rating Curve= 0 ,0
Exp/Cntr(USF)=0,0
Exp/Cntr=0.3,0.1

Type RM Length L Ch R = 1 ,6337    ,113.4,109.6,105.2
XS GIS Cut Line= 3
2178253.42193198735716.6076582412178164.14578851735644.785305556
 2178013.6716675735527.075710897
#Sta/Elev= 30
       0 1433.86       9 1433.29      17  1432.5    27.3 1432.07    57.4  1432.3
    80.1 1431.75    88.9 1431.81    99.1 1432.63   109.4 1432.59   124.7 1433.45
   129.8 1433.48   159.9 1432.58   165.3 1431.79   170.4 1430.76   175.5 1430.47
   185.6 1431.47   202.6  1430.5     206 1430.12     211 1429.97   216.9 1430.51
   224.3 1431.35   231.1 1433.08     234 1433.37   241.5 1433.23   243.8  1433.4
   246.6 1434.01   251.1  1434.4   256.8  1434.5   282.7 1436.44   305.6  1437.6
#Mann= 4 ,-1,0
       0     .06       0      50      .1       0   202.6    .045       0
   216.9     .05       0
Bank Sta=202.6,216.9
XS Rating Curve= 0 ,0
Exp/Cntr(USF)=0,0
Exp/Cntr=0.3,0.1

Type RM Length L Ch R = 1 ,6227    ,277.2,281.9,286
XS GIS Cut Line= 3
2178506.24549512 735618.318302542178409.02172542735583.648392319
2178021.18471176735449.455425498
#Sta/Elev= 30
       0 1451.52     2.2 1449.82     6.4 1448.78    14.9 1447.74    18.2 1446.91
    27.7 1442.98    33.8 1441.15    36.9  1440.8    48.9 1441.28      62  1440.7
    71.4 1440.73   116.8 1433.89   129.5  1431.3   133.7 1430.84     153 1430.51
   171.9 1430.84   184.5 1430.34   225.3 1431.08   253.6 1430.21   256.8 1430.26
   269.3 1431.71   300.8 1431.54   311.5 1432.22   324.2 1431.33   383.3 1430.51
   388.8 1429.91   398.3 1430.62   398.3 1430.63   464.3 1436.53   513.6 1438.21
#Mann= 6 ,-1,0
       0     .06       0      30     .08       0  133.22      .1       0
  383.22     .05       0   383.3    .045       0   398.3     .05       0
Bank Sta=383.3,398.3
XS Rating Curve= 0 ,0
Exp/Cntr=0.3,0.1

Type RM Length L Ch R = 1 ,5945    ,291.3,292.1,292.8
XS GIS Cut Line= 3
2178557.35896097735495.2266395592178518.54799944735448.347962401
2178212.47608663735192.164423052
#Sta/Elev= 30
       0 1447.95    10.8 1445.54    20.7 1443.53    28.6 1441.68    33.8 1440.36
    44.2 1437.19    59.1 1434.35    65.8  1433.4      79 1432.06    90.7 1431.21
   105.7 1430.65   126.5 1430.38   159.3 1430.47   214.5 1430.15     238 1430.39
   272.1 1429.97   311.8 1429.84   319.6  1429.6   333.8 1428.81   343.1 1428.84
   347.41428.288   350.8 1427.79   352.5 1427.74   357.3 1428.26   364.9  1429.4
   374.3 1430.37     397 1433.18   402.7 1433.72   439.6 1435.85     460 1436.31
#Mann= 5 ,-1,0
       0     .06       0  110.86     .05       0   347.4    .045       0
   357.3     .05       0  370.86      .1       0
Bank Sta=347.4,357.3
XS Rating Curve= 0 ,0
Exp/Cntr=0.3,0.1

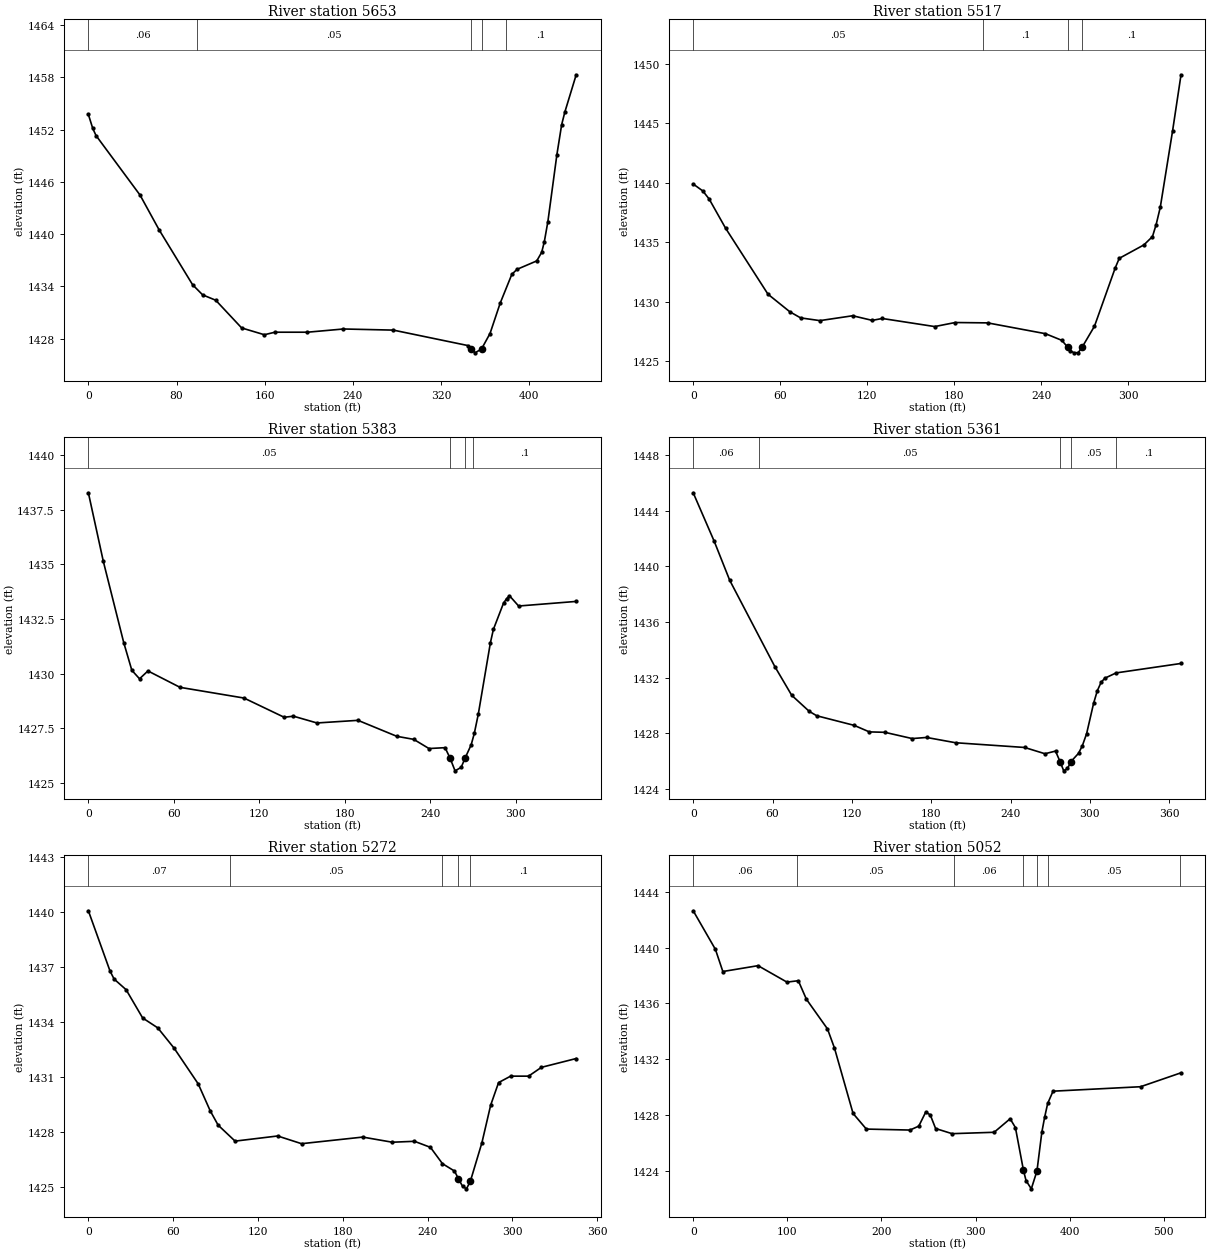
Type RM Length L Ch R = 1 ,5653    ,136.3,136.4,136.5
XS GIS Cut Line= 3
2178714.23512977735316.3309090592178675.83055313735225.501593072
2178429.75195488734984.955149702
#Sta/Elev= 30
       0 1453.74       4 1452.13       7 1451.31    46.9 1444.48    64.2 1440.49
    94.6 1434.18   103.7 1433.02   115.6  1432.4   139.1 1429.22   159.7 1428.44
   169.3 1428.73   198.8 1428.73   231.5  1429.1   276.8 1428.97   344.3  1427.2
   347.5 1426.82   350.9 1426.36   356.81426.805   364.5 1428.58   373.7 1432.06
   384.3 1435.38     389 1435.95   406.9 1436.92   411.4 1437.91   413.8 1439.14
     417 1441.43   425.2 1449.14   429.5 1452.56   432.4 1454.02   442.7  1458.3
#Mann= 5 ,-1,0
       0     .06       0   98.61     .05       0   347.5    .045       0
   356.8     .05       0  378.61      .1       0
Bank Sta=347.5,356.8
XS Rating Curve= 0 ,0
Exp/Cntr=0.3,0.1

Type RM Length L Ch R = 1 ,5517    ,133.7,133.8,133.9
XS GIS Cut Line= 2
 2178776.8532978735136.1075493492178537.72283077734899.298737346
#Sta/Elev= 30
       0  1439.9     6.6 1439.32      11 1438.64    22.3 1436.19    51.6 1430.63
    66.7 1429.15    74.1 1428.64    87.4 1428.41     110 1428.82   123.5 1428.43
   130.4 1428.59   166.6 1427.91   180.7 1428.25   203.1 1428.22     243 1427.31
   254.3 1426.75   258.2 1426.19   259.9 1425.88   262.8  1425.7   265.6 1425.72
   268.4  1426.2   276.8 1427.94   291.1 1432.84   293.9 1433.65   310.9 1434.78
   316.8 1435.48   319.3 1436.47   322.2 1437.95   330.7 1444.39   336.5 1449.09
#Mann= 4 ,-1,0
       0     .05       0     200      .1       0   258.2    .045       0
   268.4      .1       0
Bank Sta=258.2,268.4
XS Rating Curve= 0 ,0
Exp/Cntr(USF)=0,0
Exp/Cntr=0.3,0.1

Type RM Length L Ch R = 1 ,5383    ,22.5,22.2,21.9
XS GIS Cut Line= 2
 2178865.6566023735038.5980385252178624.20448026734795.985088973
#Sta/Elev= 30
       0 1438.27    10.5 1435.13    24.8 1431.42    30.5 1430.15    35.9 1429.76
    41.8 1430.12    64.3 1429.37   109.2 1428.88   137.4    1428   143.9 1428.05
   160.4 1427.74   189.2 1427.86   216.4 1427.13   228.3 1426.99     239 1426.57
   250.3 1426.61   253.8 1426.13   257.3 1425.55   261.6 1425.71   264.31426.127
   268.6 1426.74   270.8 1427.26   273.6 1428.14   282.1 1431.41   284.2 1432.02
   291.3 1433.22   293.4 1433.42   295.5 1433.56   301.9 1433.09   342.3  1433.3
#Mann= 4 ,-1,0
       0     .05       0   253.8    .045       0   264.3     .05       0
     270      .1       0
Bank Sta=253.8,264.3
XS Rating Curve= 0 ,0
Exp/Cntr(USF)=0,0
Exp/Cntr=0.3,0.1

Type RM Length L Ch R = 1 ,5361    ,88.1,89.3,90.3
XS GIS Cut Line= 2
2178905.32857276735031.997916635 2178635.4495122734780.492557376
#Sta/Elev= 30
       0 1445.28    15.9 1441.79    27.6 1438.99    61.7 1432.79    74.5 1430.72
    87.7 1429.57    93.4 1429.25   121.7 1428.56   133.2 1428.09   144.9 1428.06
   165.6 1427.61   176.5 1427.69   198.4 1427.31   250.6 1426.97     266 1426.52
     274 1426.71   277.41425.957   280.2 1425.29     283 1425.46   285.8 1425.95
   285.8 1425.97   291.4 1426.55   294.3  1427.1   297.5 1427.96   302.8 1430.15
   305.6 1431.05   308.5 1431.66   311.3 1431.95   319.8 1432.33   368.9 1433.01
#Mann= 5 ,-1,0
       0     .06       0      50     .05       0   277.4    .045       0
   285.8     .05       0     320      .1       0
Bank Sta=277.4,285.8
XS Rating Curve= 0 ,0
Exp/Cntr=0.3,0.1

Type RM Length L Ch R = 1 ,5272    ,219.8,219.2,218.7
XS GIS Cut Line= 2
2178937.11994635734973.8878761872178707.82068515734715.926207339
#Sta/Elev= 30
       0 1440.05    15.3 1436.77    18.2 1436.33    26.7 1435.75    38.4 1434.21
    49.1 1433.67    60.7 1432.56    77.7 1430.62    86.2 1429.15    91.8 1428.37
   103.8  1427.5   133.9 1427.78   150.8 1427.36   194.1 1427.72     215 1427.44
   230.7 1427.49     242 1427.16   250.5 1426.27     259 1425.87   261.8 1425.45
   264.7 1425.04   267.5  1424.9   270.3 1425.33   278.4 1427.41   284.6 1429.46
   290.2 1430.69   298.7 1431.04   311.4 1431.04   320.5 1431.52   345.1    1432
#Mann= 5 ,-1,0
       0     .07       0     100     .05       0     250      .1       0
   261.8    .045       0   270.3      .1       0
Bank Sta=261.8,270.3
XS Rating Curve= 0 ,0
Exp/Cntr(USF)=0,0
Exp/Cntr=0.3,0.1

Type RM Length L Ch R = 1 ,5052    ,153.1,152.6,152
XS GIS Cut Line= 3
 2179120.6461817734901.4505973862179074.90604079734782.550575845
2178800.85478225734503.680665579
#Sta/Elev= 30
       0 1442.65    23.6 1439.88    31.5 1438.29    68.9 1438.71    99.6 1437.53
   111.7 1437.63   120.3  1436.3   142.7 1434.17   150.1  1432.8   169.9  1428.1
     184 1426.98   230.3 1426.91   239.7 1427.19   247.1  1428.2   251.9    1428
   257.6 1427.02   275.1 1426.65   319.8 1426.75   336.8 1427.72   342.4 1427.09
   350.9 1424.04   353.7 1423.28   359.3 1422.69   365.3 1423.97   370.5 1426.76
   373.5 1427.84   376.7 1428.82   382.4  1429.7   475.4 1430.02   518.4 1431.02
#Mann= 7 ,-1,0
       0     .06       0     110     .05       0  277.39     .06       0
   350.9    .045       0   365.3     .06       0  377.39     .05       0
  517.39      .1       0
Bank Sta=350.9,365.3
XS Rating Curve= 0 ,0
Exp/Cntr=0.3,0.1

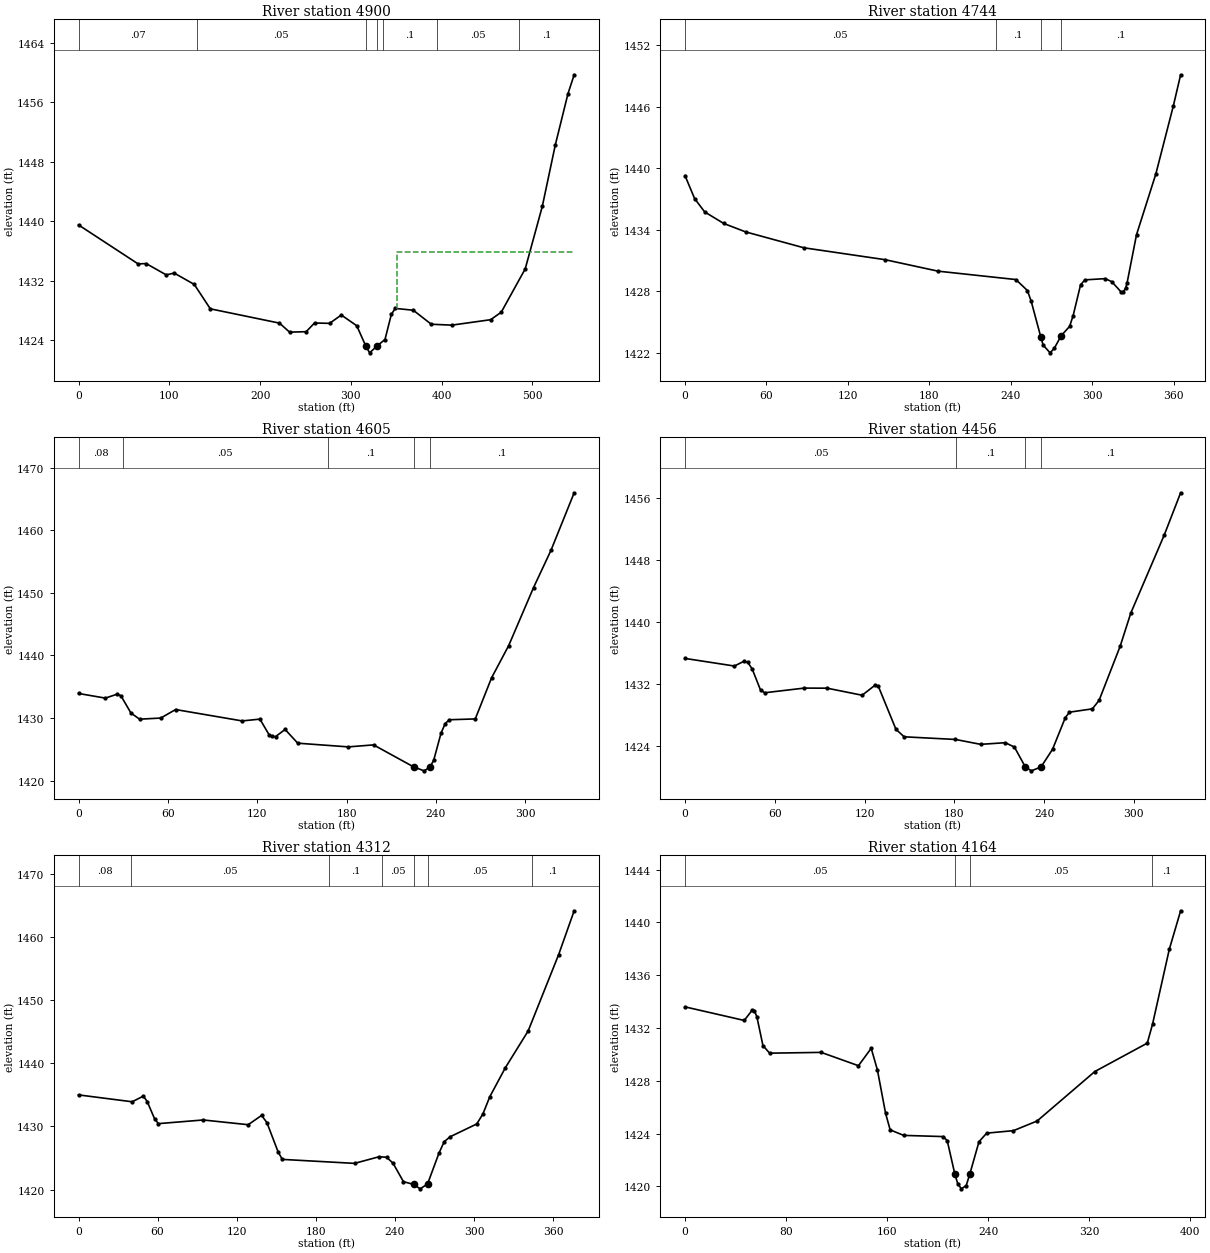
Type RM Length L Ch R = 1 ,4900    ,155.3,156.1,156.7
XS GIS Cut Line= 5
2179283.61396098734694.5468180412179148.55277768734631.099027918
     2179020.979      734510.0262178895.53199808734399.718183412
2178887.27164961734346.476506665
#Sta/Elev= 30
       0 1439.52    65.7 1434.28    74.5 1434.33    96.6 1432.81   105.4 1433.05
   127.5 1431.53   145.2 1428.25   221.4 1426.33   232.5 1425.12   250.8 1425.18
     260 1426.35   276.6  1426.3   289.5 1427.42   306.5 1425.98   316.41423.266
   320.7 1422.34   329.1 1423.29   337.6 1424.13   344.6  1427.5   348.9 1428.31
   368.8 1428.06   388.6 1426.18   411.2 1426.06     454 1426.79   465.7  1427.8
   492.1 1433.62   510.9 1442.01   525.3  1450.3   539.2 1457.15     546 1459.68
#Mann= 7 ,-1,0
       0     .07       0     130     .05       0   316.4    .045       0
   329.1     .05       0   335.1      .1       0   395.1     .05       0
   485.1      .1       0
#XS Ineff= 2 , 0
                          351.11         1435.92
Permanent Ineff=
       F       F
Bank Sta=316.4,329.1
XS Rating Curve= 0 ,0
Exp/Cntr=0.3,0.1

Type RM Length L Ch R = 1 ,4744    ,139.2,138.9,137.9
XS GIS Cut Line= 3
2179319.29576608734602.5055972562179246.76479082734521.234742037
2179069.76041549734335.918142746
#Sta/Elev= 30
       0 1439.28     7.1 1437.03    14.5 1435.73    28.6  1434.6    44.7 1433.78
    87.6 1432.23   147.4 1431.07   186.4 1429.95   243.8 1429.13   252.3 1428.06
   255.1 1427.01   262.21423.509   263.9 1422.74     269 1421.98   272.1 1422.42
   277.21423.653   283.4 1424.56     286 1425.61   291.5 1428.63   294.7  1429.1
   309.6 1429.22   314.5 1428.92   321.2 1427.94     323 1427.93   324.7 1428.31
   325.8 1428.84   332.7 1433.51   346.9 1439.42   359.8 1446.06   365.2 1449.11
#Mann= 4 ,-1,0
       0     .05       0  228.93      .1       0   262.2    .045       0
   277.2      .1       0
Bank Sta=262.2,277.2
XS Rating Curve= 0 ,0
Exp/Cntr=0.3,0.1

Type RM Length L Ch R = 1 ,4605    ,148.1,148.7,148.2
XS GIS Cut Line= 3
2179384.67128549734460.8451037272179310.13074039734383.814571567
2179148.63579255734226.230130193
#Sta/Elev= 30
       0 1433.92      18 1433.18    25.6 1433.78    28.4 1433.58    35.2  1430.8
      41 1429.81    55.2 1429.99    65.2 1431.35   109.9 1429.53   121.8 1429.82
   128.1 1427.26   130.2 1427.06   132.3 1427.02   138.7 1428.17   147.2 1425.97
   181.2 1425.38   198.1  1425.7   225.11422.168   232.1 1421.55     2361422.155
   238.5 1423.25   243.4 1427.57   246.2 1429.11     249 1429.72   266.4 1429.85
   277.3  1436.4   288.8 1441.56   305.5 1450.84   317.2 1456.79   332.8 1466.01
#Mann= 5 ,-1,0
       0     .08       0      30     .05       0  167.19      .1       0
   225.1    .045       0     236      .1       0
Bank Sta=225.1,236
XS Rating Curve= 0 ,0
Exp/Cntr=0.3,0.1

Type RM Length L Ch R = 1 ,4456    ,142.1,143.8,144.2
XS GIS Cut Line= 3
2179492.02297028734360.7717296922179442.15528588734309.761727449
2179256.40784451734127.899740585
#Sta/Elev= 30
       0  1435.3      33 1434.32    39.2 1434.91      42 1434.79    44.9 1433.95
    50.5 1431.23    53.3 1430.88    79.7 1431.48      95 1431.47   118.4 1430.56
   126.9 1431.83   129.3 1431.69     141 1426.18   146.5 1425.21   180.8 1424.87
   197.6 1424.24   214.1 1424.45   220.2 1423.89   227.41421.362   231.5 1420.83
     238 1421.33   245.7 1423.61   254.2 1427.67     257 1428.38   272.3 1428.81
   276.8  1429.9   290.9 1436.88     298 1441.14   320.4 1451.21   331.3 1456.62
#Mann= 4 ,-1,0
       0     .05       0  181.34      .1       0   227.4    .045       0
     238      .1       0
Bank Sta=227.4,238
XS Rating Curve= 0 ,0
Exp/Cntr=0.3,0.1

Type RM Length L Ch R = 1 ,4312    ,146.6,148.4,147.8
XS GIS Cut Line= 3
2179587.68309079734287.060285492 2179384.3881298 734047.52240255
2179337.90174059734006.796026272
#Sta/Elev= 30
       0 1434.98    40.7 1433.89    49.2 1434.79    52.1 1433.93    57.7  1431.2
    60.6 1430.43    94.6 1431.01   128.7 1430.26   138.9 1431.73   142.9  1430.6
   151.4 1425.96   154.6 1424.77   209.4 1424.14     228 1425.19   233.7 1425.11
   238.6 1424.17   246.5 1421.24   254.3 1420.81   259.2 1420.11   264.8 1420.89
   273.4 1425.74   277.4 1427.57   281.9 1428.35   302.1 1430.38   306.8 1431.97
     312 1434.69   323.8 1439.28   341.1  1445.1   364.2 1457.17     376 1464.12
#Mann= 7 ,-1,0
       0     .08       0      40     .05       0     190      .1       0
     230     .05       0   254.3    .045       0   264.8     .05       0
  344.18      .1       0
Bank Sta=254.3,264.8
XS Rating Curve= 0 ,0
Exp/Cntr=0.3,0.1

Type RM Length L Ch R = 1 ,4164    ,122.1,122.3,122.5
XS GIS Cut Line= 2
2179685.34520978734210.5243766622179448.23739233733898.028432633
#Sta/Elev= 30
       0  1433.6    46.9 1432.57    53.2 1433.35    54.9 1433.31    56.9 1432.85
    61.7 1430.67      67 1430.09   107.8 1430.15   137.3 1429.14   147.4 1430.46
   152.3 1428.82   158.8 1425.52   162.4 1424.28   173.1 1423.86   204.5 1423.77
   207.6 1423.45   213.51420.963   215.9 1420.19   218.8 1419.81   222.6 1420.06
   225.51420.953   232.7 1423.38   238.8 1424.03     260 1424.22   278.7 1424.95
   324.4  1428.7   365.9 1430.85   370.1  1432.3   383.3 1437.95   392.3 1440.88
#Mann= 4 ,-1,0
       0     .05       0   213.5    .045       0   225.5     .05       0
     370      .1       0
Bank Sta=213.5,225.5
XS Rating Curve= 0 ,0
Exp/Cntr(USF)=0,0
Exp/Cntr=0.3,0.1

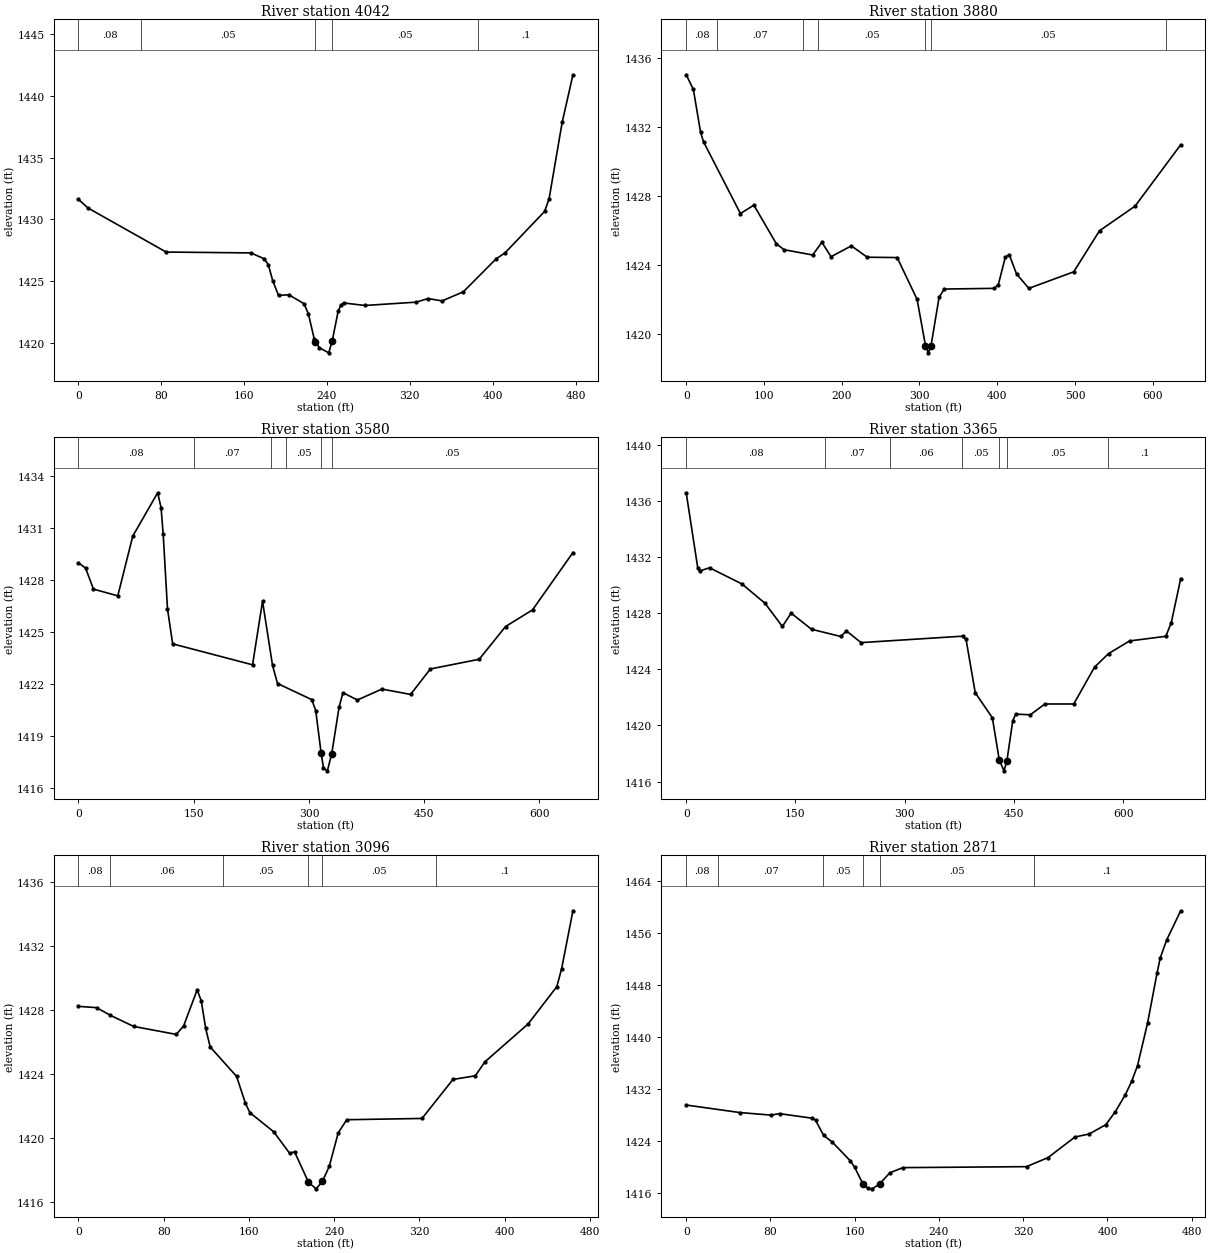
Type RM Length L Ch R = 1 ,4042    ,161.4,161.6,161.9
XS GIS Cut Line= 3
2179793.56364954734161.8868756462179573.47895744 733856.68655677
2179478.63583046733821.424368533
#Sta/Elev= 30
       0 1431.63     9.2 1430.93    84.7 1427.36   166.5 1427.29   179.2 1426.82
   183.3 1426.35   187.7 1425.01   193.2 1423.84   203.1  1423.9   217.9 1423.17
   222.1 1422.33   227.7 1420.31   228.91420.105   232.7  1419.6   241.7 1419.19
   245.1 1420.18   250.8 1422.57   253.6 1423.09   256.5 1423.23   276.6 1423.03
   326.4  1423.3   337.5 1423.59   351.2  1423.4   371.7 1424.14   403.3 1426.81
   411.8 1427.28   450.2 1430.66   454.5 1431.69   467.1 1437.87   477.5 1441.73
#Mann= 5 ,-1,0
       0     .08       0      60     .05       0   228.9    .045       0
   245.1     .05       0  386.28      .1       0
Bank Sta=228.9,245.1
XS Rating Curve= 0 ,0
Exp/Cntr(USF)=0,0
Exp/Cntr=0.3,0.1

Type RM Length L Ch R = 1 ,3880    ,300.4,299.6,293.6
XS GIS Cut Line= 4
 2179943.6411539734141.0320242612179819.83466235733934.089467646
2179702.67322734733741.448090105 2179539.6674547733695.627961175
#Sta/Elev= 30
       0 1435.05     9.2  1434.2    18.5  1431.7    22.3 1431.15    69.7 1426.98
      87 1427.47   115.8 1425.23   125.7 1424.88   162.6 1424.57   174.5 1425.31
   186.2 1424.47   212.4  1425.1   232.8 1424.44   271.3 1424.42   296.9 1421.99
307.71141419.302   311.4 1418.88314.81141419.292   325.2 1422.11   331.8 1422.59
   395.9 1422.63   401.4 1422.85   410.4 1424.45   415.4 1424.59   424.8 1423.47
   440.6 1422.63   498.3 1423.59   531.5 1425.98   577.2 1427.41   635.9 1430.98
#Mann= 7 ,-1,0
       0     .08       0      40     .07       0     150     .08       0
     170     .05       0307.7114    .045       0314.8114     .05       0
  616.62      .1       0
Bank Sta=307.7114,314.8114
XS Rating Curve= 0 ,0
Exp/Cntr=0.3,0.1

Type RM Length L Ch R = 1 ,3580    ,219.1,215.4,204.9
XS GIS Cut Line= 3
2180167.51744778733868.6675989242179797.21146212733579.452800977
2179629.41208361733534.463112537
#Sta/Elev= 30
       0 1429.01     9.3  1428.7    19.5 1427.49    51.2  1427.1    70.7 1430.55
   103.1 1433.05   107.5  1432.2   110.3 1430.65   115.9 1426.35   122.6 1424.33
   226.6 1423.12   239.6 1426.79   252.6 1423.09   259.1 1422.04   303.7 1421.11
   308.8 1420.48315.7937 1418.05   318.9 1417.17     324    1417   329.7    1418
   339.2 1420.67   344.3 1421.51   363.1 1421.09     395 1421.72   432.3 1421.41
     458 1422.88   521.6 1423.44   555.9 1425.33     591 1426.29   643.6  1429.6
#Mann= 6 ,-1,0
       0     .08       0     150     .07       0     250     .06       0
     270     .05       0315.7937    .045       0   329.7     .05       0
Bank Sta=315.7937,329.7
XS Rating Curve= 0 ,0
Exp/Cntr(USF)=0,0
Exp/Cntr=0.3,0.1

Type RM Length L Ch R = 1 ,3365    ,264.7,269.4,267.7
XS GIS Cut Line= 4
2180336.12218913733503.3334807052180017.08818149733509.122768227
2179740.67962587733492.9427552152179663.24614638733463.801675341
#Sta/Elev= 30
       0 1436.57    15.9  1431.2    18.4    1431      32 1431.23    76.4 1430.08
     108 1428.71     132 1427.05     144    1428     172 1426.85     212 1426.34
     220 1426.73     240  1425.9   379.7 1426.36   384.1 1426.13   396.7 1422.33
   420.2 1420.55429.67831417.546   436.2 1416.77440.17831417.486   448.2 1420.33
   452.2 1420.81   472.3 1420.76   492.3 1421.53   531.9 1421.53   560.4 1424.15
   579.7 1425.12   608.6 1426.02   658.3 1426.35   665.8 1427.33   678.7 1430.45
#Mann= 7 ,-1,0
       0     .08       0     190     .07       0     280     .06       0
  379.09     .05       0429.6783    .045       0440.1783     .05       0
  579.09      .1       0
Bank Sta=429.6783,440.1783
XS Rating Curve= 0 ,0
Exp/Cntr=0.3,0.1

Type RM Length L Ch R = 1 ,3096    ,223.3,224.8,222.9
XS GIS Cut Line= 4
2180179.88786728  733392.98035852180100.70460637733360.093025373
  2179827.407122733286.4469112872179742.75204099733242.961676632
#Sta/Elev= 30
       0 1428.22      17 1428.14      30 1427.66    51.7 1426.97    91.8 1426.47
    98.7    1427   111.4 1429.25   115.3 1428.55   119.4 1426.84   123.6 1425.69
   148.4 1423.85   156.7 1422.17   160.9 1421.59   183.2  1420.4   198.1 1419.06
   202.8 1419.15   215.8 1417.26     223 1416.84   228.9  1417.3   235.4 1418.25
   243.7 1420.32   251.7 1421.15   322.4 1421.23   351.4 1423.66   372.4 1423.89
   381.4 1424.76   421.9 1427.12   448.9 1429.45   453.4 1430.57     464 1434.18
#Mann= 6 ,-1,0
       0     .08       0      30     .06       0  135.74     .05       0
   215.8    .045       0   228.9     .05       0  335.74      .1       0
Bank Sta=215.8,228.9
XS Rating Curve= 0 ,0
Exp/Cntr=0.3,0.1

Type RM Length L Ch R = 1 ,2871    ,207.4,206.6,205.6
XS GIS Cut Line= 3
2180272.92550612 733225.96058447 2179877.0642886 733103.89325174
2179826.88140923733080.690844351
#Sta/Elev= 30
       0 1429.49      51 1428.33    80.3 1427.94    88.7 1428.16   119.6 1427.46
   122.8 1427.14   130.5 1424.81   138.8 1423.76   155.7 1420.91   159.8 1419.93
   167.6 1417.39   172.4 1416.64   176.6 1416.57   183.6 1417.32   193.3 1419.04
   205.7 1419.84   323.1 1419.99   343.6 1421.39   369.1 1424.56   382.7 1425.03
   398.4 1426.46   407.5 1428.48     417  1431.1     423 1433.16   428.5 1435.56
   438.1 1442.17   447.1 1449.88   450.1 1452.17   456.1 1454.91   469.5 1459.44
#Mann= 6 ,-1,0
       0     .08       0      30     .07       0     130     .05       0
   167.6    .045       0   183.6     .05       0     330      .1       0
Bank Sta=167.6,183.6
XS Rating Curve= 0 ,0
Exp/Cntr=0.3,0.1

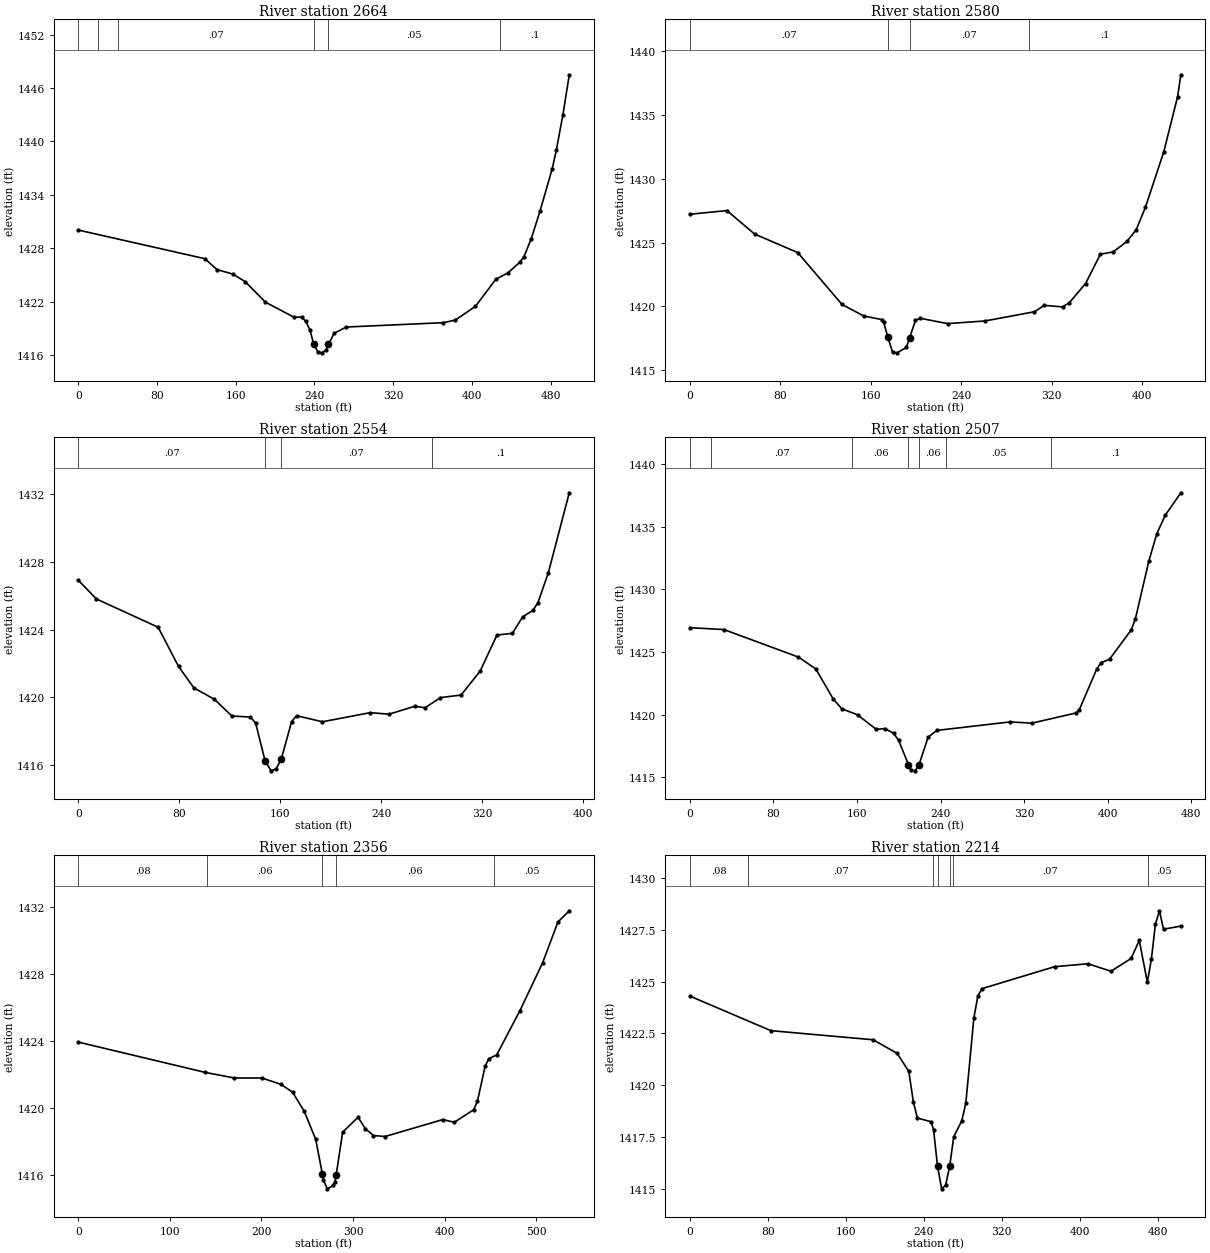
Type RM Length L Ch R = 1 ,2664    ,84.6,83.9,83.4
XS GIS Cut Line= 3
2180386.64786663733037.6019934942180303.48145477733008.179373452
2179903.39278919732915.718698111
#Sta/Elev= 30
       0 1430.04   128.6 1426.82   140.9  1425.6   157.3 1425.08   169.6 1424.24
   190.1 1421.94   218.9 1420.26   227.1 1420.24   231.2 1419.77   235.3 1418.84
   239.21417.213   243.5 1416.35   247.6 1416.24   251.7 1416.55   254.21417.185
   259.9 1418.42   272.2 1419.14   370.8 1419.63   383.1 1419.92   403.6 1421.47
   424.2  1424.5   436.5 1425.22   448.8 1426.44   452.9 1427.06   460.3 1429.07
   469.3 1432.22   481.6 1436.94   485.7    1439   492.4 1442.98   498.9 1447.49
#Mann= 6 ,-1,0
       0      .1       0      20     .08       0      40     .07       0
   239.2    .045       0   254.2     .05       0  428.22      .1       0
Bank Sta=239.2,254.2
XS Rating Curve= 0 ,0
Exp/Cntr=0.3,0.1

Type RM Length L Ch R = 1 ,2580    ,26.3,26,26.2
XS GIS Cut Line= 2
2180348.45708201732924.016665763 2179921.2725584732845.080395095
#Sta/Elev= 30
       0 1427.22    32.8 1427.51    57.2 1425.67    95.4 1424.22   134.5 1420.16
   153.7 1419.25   169.7 1418.97   171.5 1418.74   175.2 1417.57   179.3 1416.42
   183.3 1416.36   191.5 1416.78   194.51417.552   199.6 1418.91   203.7 1419.07
   228.1 1418.65   261.3 1418.86   304.8 1419.58   313.5 1420.08   329.8 1419.96
   335.7 1420.29   350.1 1421.79   363.2 1424.09   374.5 1424.27   386.7 1425.09
   394.9 1426.01     403 1427.75   419.3 1432.12   431.5 1436.43   434.4 1438.15
#Mann= 4 ,-1,0
       0     .07       0   175.2    .045       0   194.5     .07       0
     300      .1       0
Bank Sta=175.2,194.5
XS Rating Curve= 0 ,0
Exp/Cntr(USF)=0,0
Exp/Cntr=0.3,0.1

Type RM Length L Ch R = 1 ,2554    ,46.7,47.2,48
XS GIS Cut Line= 2
2180322.33846304732893.2547367532179939.84579856732821.283431144
#Sta/Elev= 30
       0 1426.92    14.4 1425.81    63.3 1424.14    79.5 1421.82    91.7 1420.55
   107.9 1419.88   121.8 1418.89   136.5 1418.83   140.6 1418.47     148 1416.26
   152.8 1415.65   156.9 1415.77   160.9 1416.34   169.1 1418.56   173.1 1418.91
   193.5 1418.55   231.4 1419.09   246.4    1419   266.8 1419.47   274.9 1419.38
   287.1 1419.98   303.4 1420.13   318.5 1421.54   331.9 1423.68   344.1 1423.78
   352.2 1424.75   360.4 1425.14   364.4  1425.6   372.6 1427.36   389.2 1432.09
#Mann= 4 ,-1,0
       0     .07       0     148    .045       0   160.9     .07       0
     280      .1       0
Bank Sta=148,160.9
XS Rating Curve= 0 ,0
Exp/Cntr(USF)=0,0
Exp/Cntr=0.3,0.1

Type RM Length L Ch R = 1 ,2507    ,150.2,150.9,151.6
XS GIS Cut Line= 4
2180365.36480016732909.9735393252180292.24502614732848.290342047
2179978.80527577 732765.707305342179929.47366688732755.687013071
#Sta/Elev= 30
       0 1426.94    32.6 1426.79     104 1424.59   120.6 1423.64   137.1 1421.26
   145.4 1420.46   160.5 1419.98   178.5 1418.81   186.7 1418.88     195  1418.5
   199.8 1417.95   209.3    1416   211.6 1415.57   215.7  1415.5   219.4 1415.99
   228.1 1418.19   236.4 1418.73   306.7 1419.41   327.4 1419.31     370 1420.13
   372.9 1420.39   389.4 1423.61   393.6 1424.13   401.8 1424.42   422.5 1426.75
   426.6 1427.66   439.4 1432.25     447 1434.43   455.1 1435.92   470.1 1437.72
#Mann= 7 ,-1,0
       0     .08       0      20     .07       0  155.66     .06       0
   209.3    .045       0   219.4     .06       0  245.66     .05       0
  345.66      .1       0
Bank Sta=209.3,219.4
XS Rating Curve= 0 ,0
Exp/Cntr=0.3,0.1

Type RM Length L Ch R = 1 ,2356    ,142.9,142.2,141.6
XS GIS Cut Line= 4
2180475.97803442732765.1068960792180342.05342876732712.821177559
2180036.62898473732614.4994861812179968.34966688732593.720476252
#Sta/Elev= 30
       0 1423.93   138.8 1422.12   170.4 1421.79   200.4 1421.79   221.3 1421.41
     234 1420.94   246.6 1419.81   259.2 1418.13   266.51416.052   267.6 1415.71
   271.8 1415.18   278.5 1415.38   280.2 1415.58   281.51415.996   288.6 1418.56
   305.4 1419.45   313.5 1418.76   322.2 1418.36   334.8  1418.3   397.9 1419.31
   410.5 1419.15   431.5 1419.89   435.7 1420.39   444.1 1422.49   448.3 1422.95
   456.7 1423.16   482.1  1425.8   506.9 1428.66   523.6 1431.09     536 1431.76
#Mann= 5 ,-1,0
       0     .08       0     140     .06       0   266.5    .045       0
   281.5     .06       0  453.77     .05       0
Bank Sta=266.5,281.5
XS Rating Curve= 0 ,0
Exp/Cntr=0.3,0.1

Type RM Length L Ch R = 1 ,2214    ,115.2,115.6,115.7
XS GIS Cut Line= 3
2180502.71989452732612.6499190792180361.16675773732564.002043355
2180018.97447211732472.595073638
#Sta/Elev= 30
       0  1424.3    83.1 1422.63     188 1422.19   212.8 1421.53   224.7 1420.66
   229.4 1419.18   233.5 1418.41   247.6 1418.23   250.1 1417.84   254.2 1416.07
   258.4 1414.99   262.5 1415.17   266.6 1416.07   270.8  1417.5   279.1 1418.28
   283.2 1419.13   291.5 1423.26   295.6 1424.31   299.8 1424.66   374.3 1425.72
   408.6 1425.86   432.2  1425.5   452.9 1426.12   461.2 1426.99   469.5 1424.97
   473.6 1426.07   477.8 1427.78   481.9 1428.42   486.1 1427.53   503.9 1427.68
#Mann= 7 ,-1,0
       0     .08       0      60     .07       0  249.68     .06       0
   254.2    .045       0   266.6     .06       0  269.68     .07       0
  469.68     .05       0
Bank Sta=254.2,266.6
XS Rating Curve= 0 ,0
Exp/Cntr=0.3,0.1