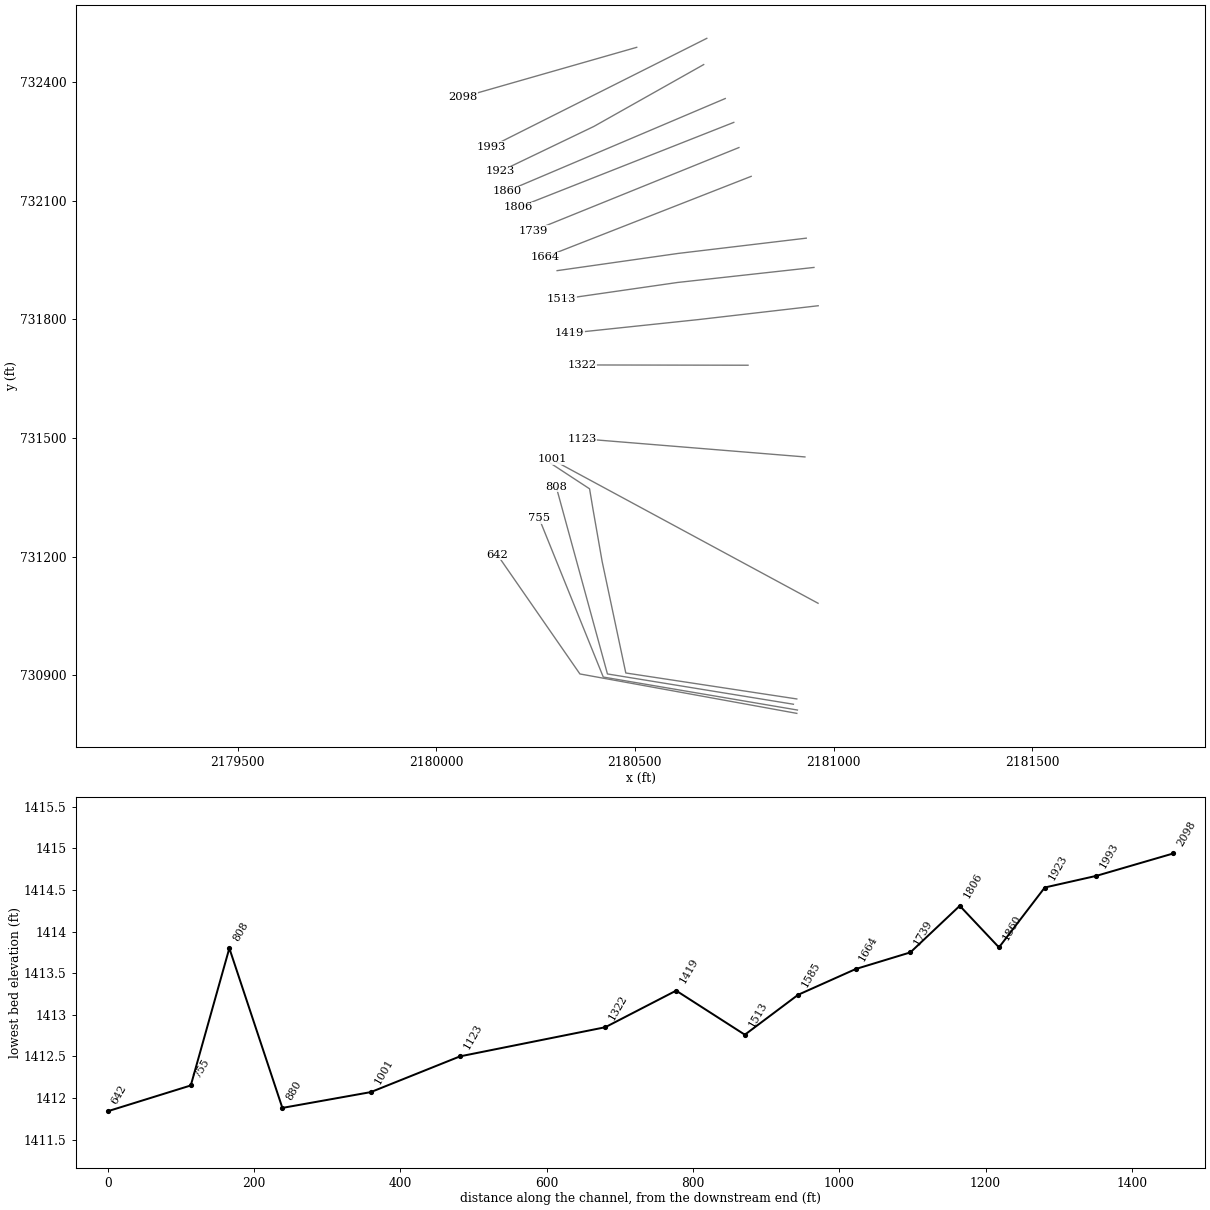
HEC-RAS study MUDLK.prj: MUDLK

--- MUDLK.g01 (geometry) --- (continued)

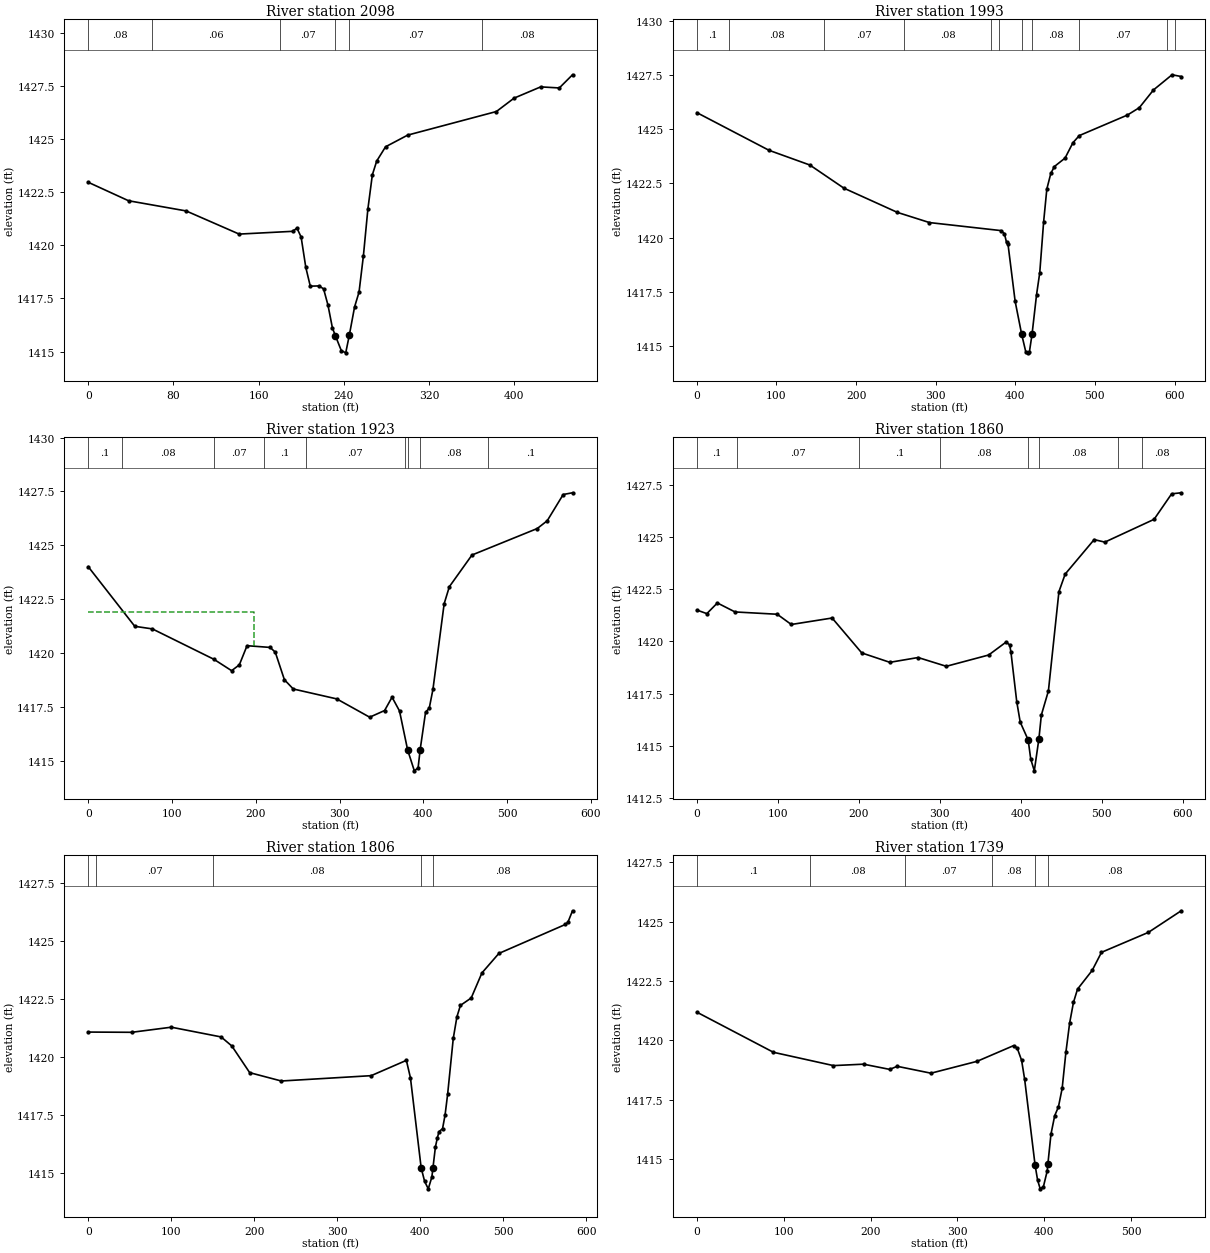
Type RM Length L Ch R = 1 ,2098    ,103,105.4,107.3
XS GIS Cut Line= 2
2180504.63996137732488.1865066652180067.42742882732362.510000194
#Sta/Elev= 30
       0 1422.97    37.9  1422.1      92 1421.62   141.8 1420.53   191.9 1420.66
   196.1 1420.81     200 1420.39   204.4 1418.96   208.6 1418.08   216.9 1418.09
   221.1 1417.95   225.2 1417.19   229.4 1416.11   232.11415.756   237.7 1415.05
   241.9 1414.94   245.3 1415.78   250.2  1417.1   254.4  1417.8   258.5 1419.51
   262.7 1421.71   266.9 1423.32     271 1423.97   279.3 1424.64   300.1 1425.19
   383.4  1426.3     400 1426.93     425 1427.46   442.5 1427.41   454.9 1428.03
#Mann= 6 ,-1,0
       0     .08       0      60     .06       0     180     .07       0
   232.1    .045       0   245.3     .07       0     370     .08       0
Bank Sta=232.1,245.3
XS Rating Curve= 0 ,0
Exp/Cntr=0.3,0.1

Type RM Length L Ch R = 1 ,1993    ,70.8,70.5,70.2
XS GIS Cut Line= 2
2180681.03896348732510.912385729 2180137.9725712732236.735329684
#Sta/Elev= 30
       0 1425.77    90.6 1424.03   141.9 1423.35   184.7 1422.28   251.9 1421.16
   292.2 1420.69   381.8 1420.32   386.3 1420.18     389 1419.77   390.8  1419.7
   399.8 1417.05     4081415.524   413.2 1414.71   415.8 1414.67   417.7 1414.71
     421 1415.52   426.7 1417.36   430.7 1418.37   435.6 1420.73   439.6 1422.24
   444.6 1422.96   449.1 1423.28   462.5 1423.67   472.4 1424.38   480.4 1424.71
   540.9 1425.66   555.8    1426   573.6 1426.82   596.9 1427.52   608.4 1427.44
#Mann= 11 ,-1,0
       0      .1       0      40     .08       0     160     .07       0
     260     .08       0     370     .07       0     380     .08       0
     408    .045       0     421     .08       0     480     .07       0
     590     .08       0     600     .07       0
Bank Sta=408,421
XS Rating Curve= 0 ,0
Exp/Cntr=0.3,0.1

Type RM Length L Ch R = 1 ,1923    ,63.1,62.6,62.5
XS GIS Cut Line= 3
2180673.19178433732444.5406239422180396.78322871732288.133831497
2180162.17304005732174.873740416
#Sta/Elev= 30
       0 1424.01    55.6 1421.24    76.6 1421.12     150 1419.71   171.2 1419.18
   180.4 1419.45   189.6 1420.34   217.2 1420.26   223.3 1420.04   234.2 1418.76
   244.8 1418.33   296.7 1417.87     336 1417.02   353.8 1417.33   362.7 1417.95
   371.6 1417.31   381.3  1415.5   389.3 1414.53   393.8 1414.67  396.23 1415.51
   402.7 1417.25   407.1 1417.44   411.5 1418.31   424.9 1422.29   431.1 1423.08
   458.1 1424.55     536 1425.78   547.9 1426.14     567 1427.36   578.1 1427.44
#Mann= 9 ,-1,0
       0      .1       0      40     .08       0     150     .07       0
     210      .1       0     260     .07       0  377.59     .08       0
   381.3    .045       0  396.23     .08       0  477.59      .1       0
#XS Ineff= 2 , 0
          197.41 1421.89
Permanent Ineff=
       F       F
Bank Sta=381.3,396.23
XS Rating Curve= 0 ,0
Exp/Cntr(USF)=0,0
Exp/Cntr=0.3,0.1

Type RM Length L Ch R = 1 ,1860    ,53.9,53.6,53.2
XS GIS Cut Line= 2
2180727.46869629732358.679461613 2180177.3482539732124.069272945
#Sta/Elev= 30
       0  1421.5    12.3 1421.33    25.3 1421.84    47.1 1421.41    99.2  1421.3
   116.6 1420.81     167 1421.12   203.6 1419.45   238.3    1419   273.2 1419.23
     308 1418.81   360.3 1419.35   381.9 1419.97   386.3 1419.83   387.8  1419.5
     395 1417.12   399.3 1416.14   409.1 1415.29   412.3 1414.37   416.7 1413.81
   422.41415.352   425.4 1416.48   434.1 1417.63   447.1 1422.38   454.8 1423.22
   490.6 1424.87   503.8 1424.75   564.6 1425.84   586.3 1427.06   598.1 1427.11
#Mann= 8 ,-1,0
       0      .1       0      50     .07       0     200      .1       0
     300     .08       0   409.1    .045       0   422.4     .08       0
     520      .1       0     550     .08       0
Bank Sta=409.1,422.4
XS Rating Curve= 0 ,0
Exp/Cntr(USF)=0,0
Exp/Cntr=0.3,0.1

Type RM Length L Ch R = 1 ,1806    ,67.3,67.5,67.5
XS GIS Cut Line= 2
2180748.97438692732298.3756144872180206.68871132732083.407557116
#Sta/Elev= 30
       0 1421.07    52.5 1421.06   100.1 1421.28   160.1 1420.86     173 1420.47
   194.5 1419.32   232.6 1418.96   340.8 1419.19   383.2 1419.85   388.1  1419.1
     401 1415.22   405.2 1414.63   409.6 1414.31   413.9 1414.82   415.2 1415.21
   418.2 1416.12   420.6 1416.52   422.5 1416.77   426.8 1416.91   429.8 1417.49
   432.9 1418.39   439.7  1420.8   444.1 1421.73   448.3 1422.22   461.3 1422.54
   474.2 1423.62   494.6 1424.46   574.7 1425.71   577.7  1425.8   583.3  1426.3
#Mann= 5 ,-1,0
       0     .08       0      10     .07       0     150     .08       0
     401    .045       0   415.2     .08       0
Bank Sta=401,415.2
XS Rating Curve= 0 ,0
Exp/Cntr(USF)=0,0
Exp/Cntr=0.3,0.1

Type RM Length L Ch R = 1 ,1739    ,74.8,74.7,74.5
XS GIS Cut Line= 2
2180761.89595188732234.7262222342180245.19790821732024.629801407
#Sta/Elev= 30
       0 1421.19    88.2  1419.5   157.3 1418.94   191.9    1419   222.1 1418.78
   230.7 1418.91   269.6 1418.62   322.7 1419.12   364.7 1419.78   368.9 1419.68
     374 1419.16   377.5 1418.36   389.51414.753   392.4 1414.12   395.4 1413.75
   399.1 1413.84   403.4 1414.49   404.21414.778   407.8 1416.05   412.1 1416.83
   416.4  1417.2   420.7 1417.98     425  1419.5   429.3 1420.73   433.7  1421.6
   438.4 1422.16   455.3 1422.95     466 1423.71     520 1424.55   557.8 1425.46
#Mann= 6 ,-1,0
       0      .1       0     130     .08       0     240     .07       0
     340     .08       0   389.5    .045       0   404.2     .08       0
Bank Sta=389.5,404.2
XS Rating Curve= 0 ,0
Exp/Cntr=0.3,0.1

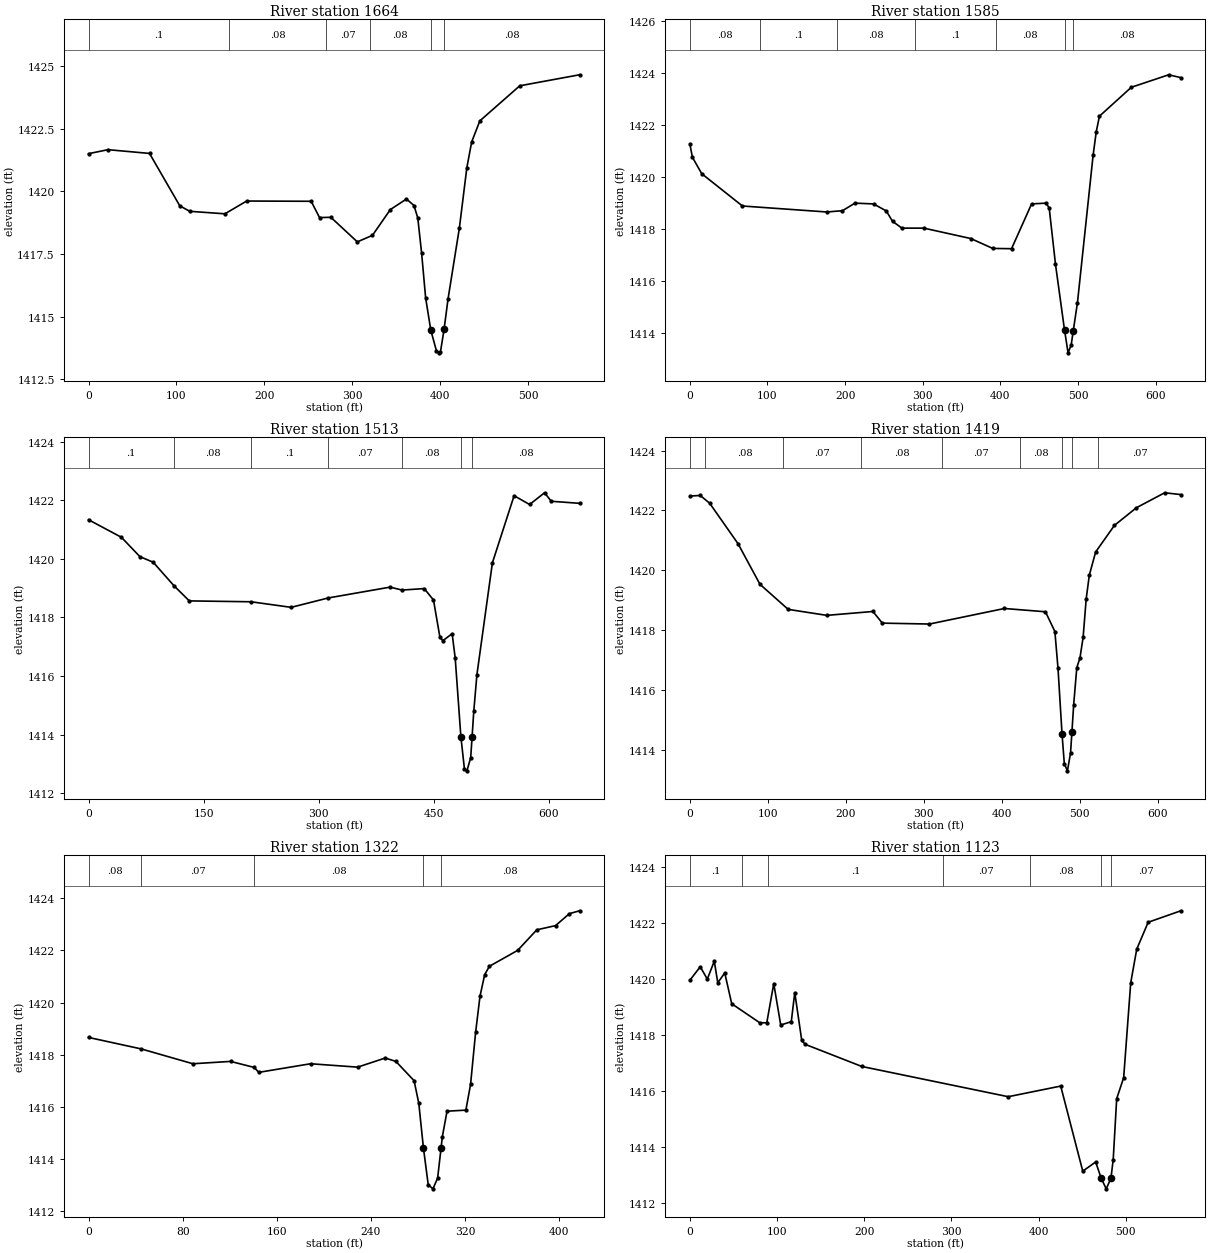
Type RM Length L Ch R = 1 ,1664    ,81,78.8,75.8
XS GIS Cut Line= 2
2180792.73461091732161.9044970622180272.95017891731957.394425499
#Sta/Elev= 30
       0  1421.5    22.1 1421.66    69.4 1421.51   103.8 1419.42   115.1  1419.2
   155.2  1419.1   179.9 1419.61   253.3  1419.6   262.8 1418.95   275.7 1418.96
   305.8 1417.98     323 1418.24   343.4 1419.27   361.7 1419.69   370.3 1419.43
   374.6 1418.93   378.9 1417.55   383.5 1415.75   389.41414.455   395.8 1413.63
   398.9 1413.55   400.4 1413.59   404.51414.486     409  1415.7   421.9 1418.53
   430.4 1420.94   435.9 1421.97   445.2 1422.81   490.6 1424.21   558.6 1424.65
#Mann= 6 ,-1,0
       0      .1       0     160     .08       0     270     .07       0
     320     .08       0   389.4    .045       0   404.5     .08       0
Bank Sta=389.4,404.5
XS Rating Curve= 0 ,0
Exp/Cntr=0.3,0.1

Type RM Length L Ch R = 1 ,1585    ,73,72.8,72.8
XS GIS Cut Line= 3
2180931.39233501732005.6067309242180609.11437307731967.035012398
2180304.29378871731923.464276343
#Sta/Elev= 30
       0 1421.26     3.3 1420.75    15.3 1420.12    67.7 1418.88   176.5 1418.65
   196.6  1418.7   212.7 1418.99   236.6 1418.96     253 1418.69   261.1 1418.29
   273.2 1418.03   301.4 1418.03   361.9 1417.63   390.2 1417.25   414.4 1417.24
   440.2 1418.96   458.9 1418.99   462.9  1418.8     471 1416.64   482.6 1414.12
   487.2 1413.24   491.2 1413.54   493.91414.088   499.3 1415.17   519.5 1420.84
   523.5 1421.73   527.6 1422.33   568.7 1423.44   616.9 1423.92   632.5 1423.81
#Mann= 7 ,-1,0
       0     .08       0      90      .1       0     190     .08       0
     290      .1       0  394.58     .08       0   482.6    .045       0
   493.9     .08       0
Bank Sta=482.6,493.9
XS Rating Curve= 0 ,0
Exp/Cntr(USF)=0,0
Exp/Cntr=0.3,0.1

Type RM Length L Ch R = 1 ,1513    ,94.1,93.9,93.4
XS GIS Cut Line= 3
2180950.80316915731931.5784178932180607.65753248731893.594240391
2180315.72560271731851.328001401
#Sta/Elev= 30
       0 1421.33    42.9 1420.73      67 1420.07    84.3 1419.88   111.3 1419.08
   131.4 1418.56   211.9 1418.53   264.2 1418.34   312.5 1418.66   393.2 1419.03
   408.7 1418.93   437.7 1418.98   449.8 1418.59   458.1 1417.33   461.9  1417.2
   474.1 1417.44   478.1 1416.61   485.51413.927   490.2 1412.81   493.4 1412.76
   498.3 1413.21   500.1 1413.91   502.3 1414.79   506.4 1416.04   526.6 1419.86
   554.9 1422.15   575.1 1421.85   594.6 1422.25   603.4 1421.96   640.2 1421.89
#Mann= 7 ,-1,0
       0      .1       0   111.3     .08       0   211.9      .1       0
   312.5     .07       0   408.7     .08       0   485.5    .045       0
   500.1     .08       0
Bank Sta=485.5,500.1
XS Rating Curve= 0 ,0
Exp/Cntr(USF)=0,0
Exp/Cntr=0.3,0.1

Type RM Length L Ch R = 1 ,1419    ,98.2,96.9,95.5
XS GIS Cut Line= 3
2180961.42669733731834.7126034812180659.88180934 731799.71123841
2180335.47796616731765.345706769
#Sta/Elev= 30
       0 1422.48    13.3  1422.5    25.4 1422.24    61.7 1420.89    89.9 1419.53
   126.1 1418.69   175.7 1418.49   234.8 1418.62   246.9 1418.23   307.3  1418.2
   403.5 1418.72   456.1 1418.61   468.2 1417.95   472.2 1416.72477.39261414.516
   480.3 1413.53   484.3 1413.29   488.3 1413.89490.09261414.601   492.3  1415.5
   496.3 1416.74   500.4 1417.07   504.4 1417.75   508.4 1419.05   512.4 1419.84
   520.5 1420.61   544.6  1421.5   572.8 1422.09     609 1422.59   629.8 1422.53
#Mann= 9 ,-1,0
       0      .1       0      20     .08       0     120     .07       0
     220     .08       0  323.57     .07       0  423.57     .08       0
477.3926    .045       0490.0926     .08       0  523.57     .07       0
Bank Sta=477.3926,490.0926
XS Rating Curve= 0 ,0
Exp/Cntr=0.3,0.1

Type RM Length L Ch R = 1 ,1322    ,199.8,198.5,197.2
XS GIS Cut Line= 2
2180784.87886556 731684.303587392180367.57592976731684.989256838
#Sta/Elev= 30
       0 1418.66    44.7 1418.22    88.7 1417.65   120.7 1417.74   140.7 1417.51
   144.7 1417.32   188.7 1417.65   228.7 1417.52   252.2 1417.87   261.2 1417.74
   276.7    1417   280.7 1416.13   284.61414.433   288.7 1413.01   292.7 1412.85
   296.7 1413.26   299.6 1414.41   300.7 1414.85   304.7 1415.83   320.7 1415.87
   324.7 1416.86     329 1418.86   332.7 1420.24   336.7 1421.07   340.7 1421.39
   364.7    1422     381 1422.79   396.9 1422.95   408.7 1423.41   417.3 1423.52
#Mann= 5 ,-1,0
       0     .08       0    44.7     .07       0   140.7     .08       0
   284.6    .045       0   299.6     .08       0
Bank Sta=284.6,299.6
XS Rating Curve= 0 ,0
Exp/Cntr=0.3,0.1

Type RM Length L Ch R = 1 ,1123    ,125.8,122,117.2
XS GIS Cut Line= 2
2180928.05872678731452.391098181  2180366.800024731498.368033899
#Sta/Elev= 30
       0 1419.95    11.9 1420.43      20 1419.99      28 1420.63      32 1419.86
      40 1420.21      48 1419.11    80.2 1418.43    88.2 1418.43    96.2 1419.83
   104.2 1418.35   116.3 1418.47   120.3 1419.51   128.3  1417.8   132.3 1417.66
   197.2 1416.87   365.1 1415.79   425.3 1416.17   450.6 1413.13   465.4 1413.46
   471.7 1412.88   477.5  1412.5   482.9 1412.88   485.5 1413.54   489.5 1415.72
   497.5 1416.47   505.6 1419.86   512.5 1421.06   525.6 1422.02   563.1 1422.43
#Mann= 7 ,-1,0
       0      .1       0      60     .08       0      90      .1       0
     290     .07       0     390     .08       0   471.7    .045       0
   482.9     .07       0
Bank Sta=471.7,482.9
XS Rating Curve= 0 ,0
Exp/Cntr=0.3,0.1

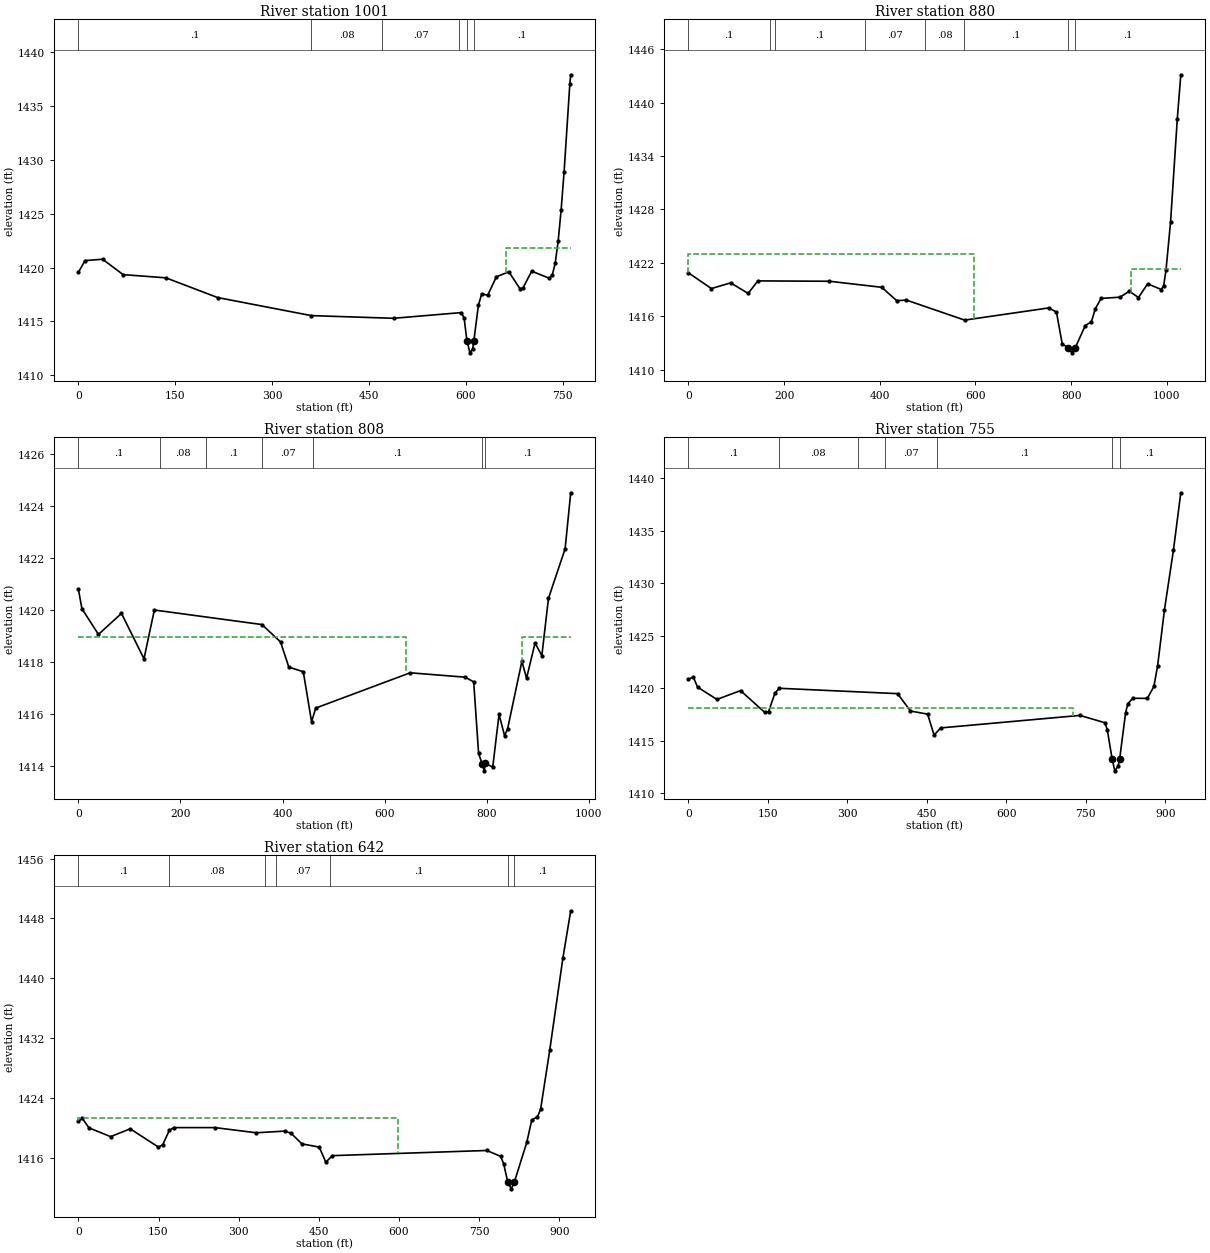
Type RM Length L Ch R = 1 ,1001    ,137.3,120.9,80.9
XS GIS Cut Line= 2
2180961.10923364731082.3732161972180291.12765714731445.938536293
#Sta/Elev= 30
       0 1419.54    10.2 1420.64    37.5 1420.77    69.3 1419.34   135.5 1419.04
   215.5 1417.21   360.6 1415.53     488 1415.28   592.8 1415.81   597.2 1415.32
   601.6 1413.19   606.3 1412.07   610.5 1412.44   612.3 1413.18   619.3 1416.47
   624.5 1417.56   633.7 1417.42   647.3 1419.14   666.5  1419.6   683.7 1418.03
   688.3 1418.09   701.9 1419.66   729.2    1419   733.8  1419.3   738.3 1420.41
   742.9 1422.49   747.4 1425.31     752 1428.85   760.9 1437.05   762.3 1437.91
#Mann= 6 ,-1,0
       0      .1       0     360     .08       0     470     .07       0
     590      .1       0   601.6    .045       0   612.3      .1       0
#XS Ineff= 2 , 0
                          662.08         1421.83
Permanent Ineff=
       F       F
Bank Sta=601.6,612.3
XS Rating Curve= 0 ,0
Exp/Cntr(USF)=0,0
Exp/Cntr=0.3,0.1

Type RM Length L Ch R = 1 ,880     ,68.5,72.5,93.7
XS GIS Cut Line= 6
2180907.60798252730840.4016486422180477.16609853730906.062275014
2180417.58515978731188.159780907 2180394.4823468731320.696971177
2180385.97078412731371.7663472442180286.26390704731437.426973615
#Sta/Elev= 30
       0 1420.88      48 1419.11    88.4 1419.75   124.9 1418.56   145.1 1419.97
   294.8 1419.93   404.2 1419.25   435.4 1417.75   455.8 1417.81   577.6 1415.56
   753.2 1416.93   769.4 1416.47   781.6 1412.86   793.8 1412.48   801.8 1411.88
   808.8 1412.45   829.6 1414.95   842.5 1415.37   850.6 1416.83   862.8    1418
   902.4 1418.14   921.8 1418.81   940.9  1418.1   960.1 1419.64   988.8    1419
   993.6 1419.45   998.4 1421.14    1008 1426.58  1022.1 1438.22  1029.4 1443.15
#Mann= 8 ,-1,0
       0      .1       0     170     .08       0     180      .1       0
     370     .07       0  495.42     .08       0  575.42      .1       0
   793.8    .045       0   808.8      .1       0
#XS Ineff= 2 , 0
          596.96    1423   926.2         1421.26
Permanent Ineff=
       F       F
Bank Sta=793.8,808.8
XS Rating Curve= 0 ,0
Exp/Cntr(USF)=0,0
Exp/Cntr=0.3,0.1

Type RM Length L Ch R = 1 ,808     ,50.6,52.7,54.5
XS GIS Cut Line= 3
2180899.09641984730827.0263358622180430.96047256730903.630399963
2180302.07109487731376.630097345
#Sta/Elev= 30
       0 1420.81       7 1420.05    39.4 1419.06    84.5 1419.87   128.6 1418.12
   148.9    1420   359.6 1419.44   396.1 1418.77   412.3  1417.8   440.7 1417.62
   456.9 1415.69     465 1416.22   650.1 1417.58   758.1 1417.41   774.5 1417.23
   784.1 1414.47   791.1 1414.07   795.2  1413.8   797.4 1414.09   811.8 1413.94
   824.2 1415.98   834.9 1415.16   840.8 1415.41   868.9 1418.02   878.1 1417.37
   894.7 1418.73     908 1418.24     921 1420.45   953.6 1422.36   964.6 1424.52
#Mann= 7 ,-1,0
       0      .1       0     160     .08       0     250      .1       0
     360     .07       0     460      .1       0   791.1    .045       0
   797.4      .1       0
#XS Ineff= 2 , 0
          641.69 1418.95  869.86         1418.97
Permanent Ineff=
       F       F
Bank Sta=791.1,797.4
XS Rating Curve= 0 ,0
Exp/Cntr(USF)=0,0
Exp/Cntr=0.3,0.1

Type RM Length L Ch R = 1 ,755     ,110.6,113.5,115
XS GIS Cut Line= 3
2180909.18419783730812.3683674492180420.47405387730895.766002936
2180258.68264103731297.742605985
#Sta/Elev= 30
       0 1420.85     9.1 1421.08    17.3 1420.11    53.8 1418.94    98.4 1419.78
   143.7 1417.72   151.2 1417.78   163.3 1419.54   171.4    1420   394.6 1419.49
     419 1417.84   451.4 1417.54   463.6 1415.54   475.8 1416.23   738.8 1417.42
   786.2 1416.72   790.5 1416.02   799.41413.323   804.5 1412.15   810.7 1412.57
   813.8  1413.3     825 1417.69   829.1 1418.52   838.4 1419.05     866 1419.04
   878.3 1420.17   885.4 1422.15   898.3 1427.47   915.2 1433.13   929.1 1438.59
#Mann= 7 ,-1,0
       0      .1       0     170     .08       0     320      .1       0
     370     .07       0     470      .1       0   799.4    .045       0
   813.8      .1       0
#XS Ineff= 2 , 0
          726.36 1418.08
Permanent Ineff=
       F       F
Bank Sta=799.4,813.8
XS Rating Curve= 0 ,0
Exp/Cntr(USF)=0,0
Exp/Cntr=0.3,0.1

Type RM Length L Ch R = 1 ,642     ,211.4,221.6,231.2
XS GIS Cut Line= 3
2180907.60798252730803.9235228792180361.65203361730903.630399963
2180153.72671677731205.182906263
#Sta/Elev= 30
       0 1420.88     7.6 1421.25    19.8    1420    60.4 1418.82      97 1419.87
   149.9 1417.42     158 1417.75   170.2 1419.66   178.3 1420.03   255.6 1420.03
   332.8 1419.34   385.8 1419.56   397.9 1419.28   418.2 1417.86   450.8 1417.42
     463  1415.4   475.2 1416.28   764.2 1416.97   790.1 1416.19   795.9 1415.18
   803.51412.725   810.2 1411.84     816 1412.79     839 1418.04   848.4 1421.05
   859.1 1421.48   864.9 1422.47   882.1 1430.42   906.7 1442.73   921.3 1449.03
#Mann= 7 ,-1,0
       0      .1       0     170     .08       0     350      .1       0
     370     .07       0     470      .1       0   803.5    .045       0
     816      .1       0
#XS Ineff= 2 , 0
          598.87 1421.27
Permanent Ineff=
       F       F
Bank Sta=803.5,816
XS Rating Curve= 0 ,0
Exp/Cntr(USF)=0,0
Exp/Cntr=0.3,0.1