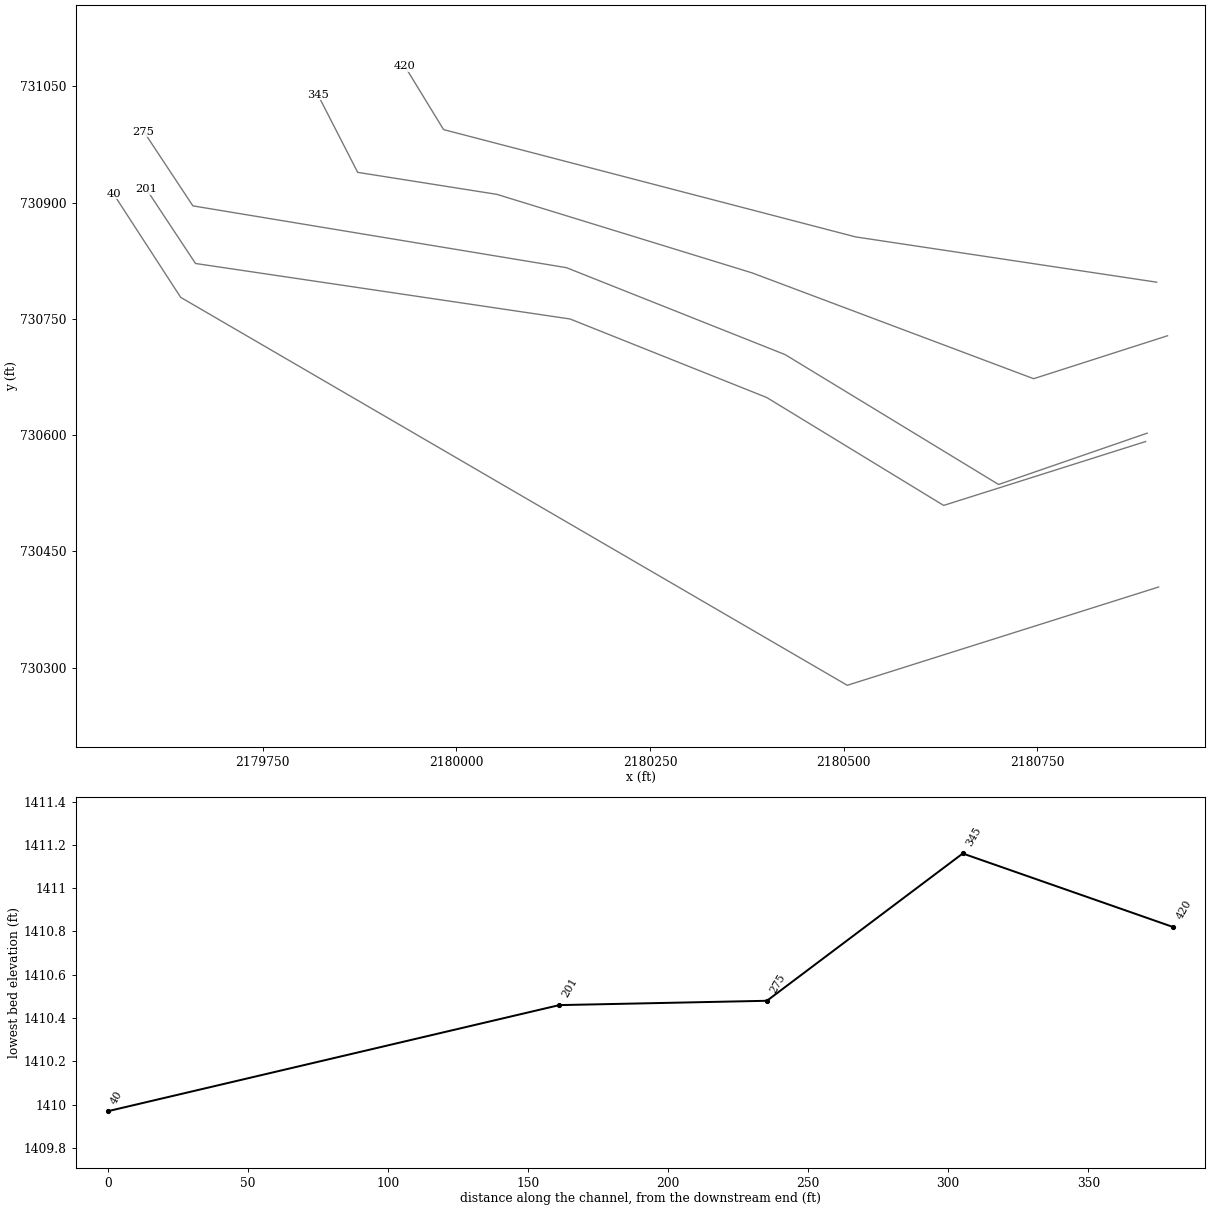
HEC-RAS study MUDLK.prj: MUDLK

--- MUDLK.g01 (geometry) --- (continued)

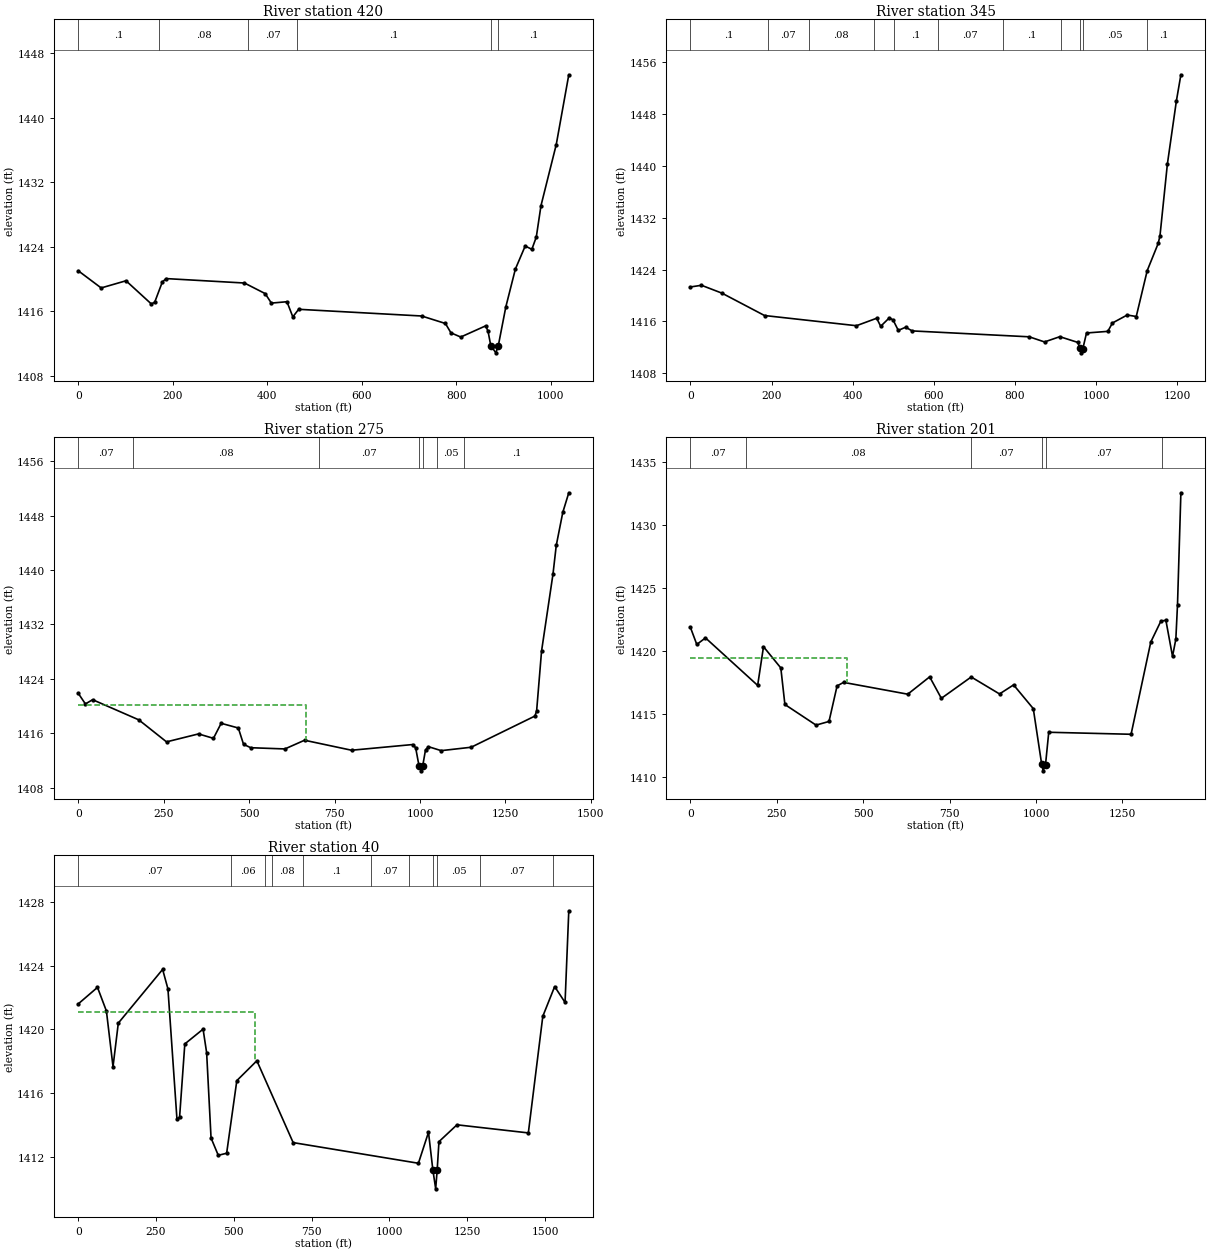
Type RM Length L Ch R = 1 ,420     ,75.9,75.2,73.8
XS GIS Cut Line= 4
 2180904.1803397730797.3567930612180515.54735833730855.735137902
2179983.47044392730994.1752128112179933.43186263731075.904895589
#Sta/Elev= 30
       0    1421    48.5 1418.87   101.1 1419.76   154.6 1416.89   161.8 1417.09
     178 1419.61   186.1 1420.03   351.9 1419.48   395.7 1418.17   408.9 1416.99
   441.9 1417.16   454.3 1415.28   466.7 1416.22   727.1 1415.39   777.4 1414.46
   789.1  1413.3   809.8 1412.78   862.7 1414.17   867.7 1413.48  873.39 1411.72
   884.2 1410.82   889.41411.717   905.3 1416.52   925.5 1421.21   946.3 1424.07
   960.4 1423.66   969.8 1425.18   979.7 1429.07    1012 1436.64  1038.6 1445.31
#Mann= 6 ,-1,0
       0      .1       0     170     .08       0     360     .07       0
  462.99      .1       0  873.39    .045       0   889.4      .1       0
Bank Sta=873.39,889.4
XS Rating Curve= 0 ,0
Exp/Cntr(USF)=0,0
Exp/Cntr=0.3,0.1

Type RM Length L Ch R = 1 ,345     ,70.6,69.9,68.9
XS GIS Cut Line= 6
2180918.29051797730728.2516691852180745.35718103730672.858959694
 2180381.9269651730809.3141708782180052.27279154730910.642297995
2179872.58424612730939.0141735882179821.24466172 731038.99125901
#Sta/Elev= 30
       0 1421.31    27.4 1421.57    77.8 1420.36   182.8 1416.91   409.3 1415.34
   459.2 1416.49   469.1 1415.25   490.5 1416.56   499.6 1416.23   512.5 1414.62
   530.7 1415.11   546.6 1414.54   835.3 1413.63   872.9 1412.84   910.6 1413.65
   955.3 1412.76   959.8 1411.83   963.4 1411.16   967.4 1411.82   976.4 1414.22
  1028.9 1414.47  1040.3 1415.76  1076.7 1416.99    1099 1416.76    1126 1423.83
    1153 1428.01  1157.5 1429.22  1175.7 1440.25  1197.9 1449.98    1209 1454.01
#Mann= 11 ,-1,0
       0      .1       0  191.59     .07       0  291.59     .08       0
  451.59     .07       0  501.59      .1       0  609.79     .07       0
  769.79      .1       0  914.67     .05       0   959.8    .045       0
   967.4     .05       0 1126.58      .1       0
Bank Sta=959.8,967.4
XS Rating Curve= 0 ,0
Exp/Cntr(USF)=0,0
Exp/Cntr=0.3,0.1

Type RM Length L Ch R = 1 ,275     ,73.4,74.1,74.7
XS GIS Cut Line= 6
2180891.94520492730602.6047915592180700.09728425730536.403748509
2180424.48477849730703.9329186762180142.11706425730816.069379353
2179659.79517918730895.7808393512179596.29621952730991.704799689
#Sta/Elev= 30
       0 1421.88    20.9 1420.32    42.1 1420.94   177.1 1417.98   258.3 1414.74
   351.9 1415.91   395.6 1415.26   418.2 1417.47   468.4 1416.78   483.7 1414.38
   504.8 1413.88   604.7  1413.7   662.2 1414.98   799.8 1413.51   979.2 1414.35
   987.4 1413.86   997.21411.215  1003.8 1410.48    1008 1411.21  1016.2 1413.56
  1024.9 1414.03  1062.1 1413.45  1149.8 1413.95  1336.5 1418.54  1341.4 1419.31
  1355.8 1428.09  1389.3 1439.43  1398.8 1443.62    1418  1448.5  1435.5 1451.37
#Mann= 7 ,-1,0
       0     .07       0     160     .08       0  705.48     .07       0
   997.2    .045       0    1008     .07       0  1049.3     .05       0
  1129.3      .1       0
#XS Ineff= 2 , 0
          667.04 1420.21
Permanent Ineff=
       F       F
Bank Sta=997.2,1008
XS Rating Curve= 0 ,0
Exp/Cntr(USF)=0,0
Exp/Cntr=0.3,0.1

Type RM Length L Ch R = 1 ,201     ,161.2,161.2,161.2
XS GIS Cut Line= 6
2180889.91864238   730591.7964582180629.16759526730509.382914612
2180400.84154883730648.5402091862180146.84571019730749.868336303
2179663.17278341730821.4735461322179599.67382375 730917.39750647
#Sta/Elev= 30
       0 1421.89    18.6 1420.52    43.8 1421.04   194.7 1417.26   211.6 1420.34
   261.7 1418.65   273.5 1415.74   363.6  1414.1   401.1 1414.39   424.5 1417.22
   443.3  1417.5   628.9 1416.56   692.3 1417.94   726.1 1416.23   812.5 1417.93
   894.4 1416.58   935.1  1417.3   992.1 1415.41  1016.41410.977  1020.6 1410.46
  1027.51410.958  1036.8 1413.53    1275 1413.37    1332 1420.71  1361.3 1422.38
  1375.7 1422.44  1394.9 1419.57  1404.5 1420.94  1409.3 1423.68  1419.1 1432.59
#Mann= 6 ,-1,0
       0     .07       0     160     .08       0  810.86     .07       0
  1016.4    .045       0  1027.5     .07       0 1364.09      .1       0
#XS Ineff= 2 , 0
          452.51 1419.42
Permanent Ineff=
       F       F
Bank Sta=1016.4,1027.5
XS Rating Curve= 0 ,0
Exp/Cntr(USF)=0,0
Exp/Cntr=0.3,0.1

Type RM Length L Ch R = 1 ,40      ,,,
XS GIS Cut Line= 4
2180906.68712022730404.1454015412180504.71051718730277.380995601
2179644.04691895730777.7668085242179557.31337804730911.203025304
#Sta/Elev= 30
       0 1421.61    61.8 1422.65    90.5 1421.16   111.7 1417.66   128.7  1420.4
   271.1 1423.78   288.2 1422.55   317.2 1414.34   325.6 1414.48   342.4 1419.09
   401.1 1420.02   412.5 1418.54   426.7 1413.17   449.9 1412.08   476.8 1412.21
   509.5 1416.78   573.9 1418.03   690.5 1412.88    1093 1411.58  1125.4 1413.53
  1139.3 1411.18  1148.5 1409.97  1153.3 1411.16    1159 1412.94  1216.9    1414
  1446.2 1413.49  1492.7 1420.83  1530.8  1422.7  1564.2  1421.71576.192 1427.47
#Mann= 11 ,-1,0
       0     .07       0  491.49     .06       0  601.49     .07       0
  621.49     .08       0  721.49      .1       0  941.49     .07       0
 1061.49     .05       0  1139.3    .045       0  1153.3     .05       0
 1291.49     .07       0 1527.04      .1       0
#XS Ineff= 2 , 0
          568.79 1421.12
Permanent Ineff=
       F       F
Bank Sta=1139.3,1153.3
XS Rating Curve= 0 ,0
Exp/Cntr(USF)=0,0
Exp/Cntr=0.3,0.1
LCMann Table=0

Chan Stop Cuts=-1
Use User Specified Reach Order=0
Composite Channel Slope=5